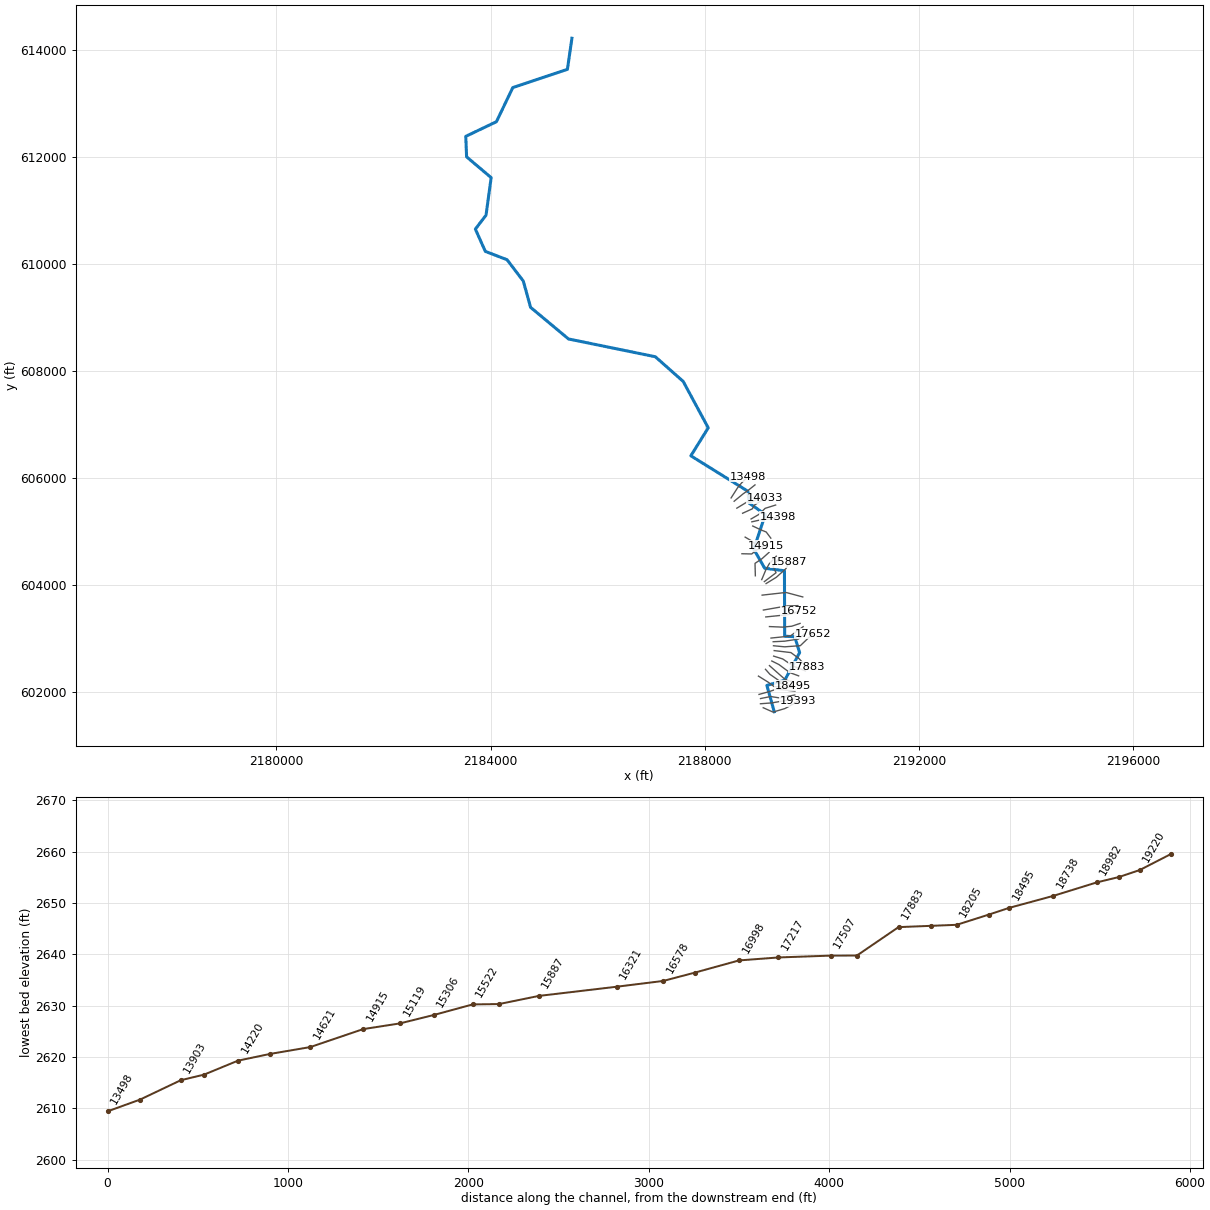
--- MARSHFK.prj (project) ---

Proj Title=MARSHFK
Current Plan=p01
Default Exp/Contr=0,0
English Units
Geom File=g01
Flow File=f01
Plan File=p01
Background Map Layer=Inundation Boundary (P100yr Value_0)
BEGIN DESCRIPTION:
----------MODEL BY WOOD PLC 2022----------
AFH study
Randolph County, WV
HEC-RAS Version: RAS 6.2
Vertical Datum: NAVD88
Projection: NAD 1983 StatePlane West Virginia S FIPS 4702 (US Feet)
Terrain: 1-meter LIDAR (FEMA Region III 3DEP collected 2016-2018)
Land Use: 2019 NLCD
Hydrologic Method:
WV SIR2010-5033 regression equations
Additional Model Notes:
KWSE at downstream boundary with RFBUCKHRV
END DESCRIPTION:
DSS Export Rating Curves= 0
DSS Export Rating Curve Sorted= 0
DSS Export Volume Flow Curves= 0
DXF OffsetX= 0
DXF OffsetY= 0
DXF ScaleX= 0
DXF ScaleY= 0

--- MARSHFK.p01 (plan) ---

Plan Title=Floodplain
Program Version=6.20
Short Identifier=Floodplain
Geom File=g01
Flow File=f01
Subcritical Flow
K Sum by GR= 0
Std Step Tol= 0.01
Critical Tol= 0.01
Num of Std Step Trials= 20
Max Error Tol= 0.3
Flow Tol Ratio= 0.001
Split Flow NTrial= 30
Split Flow Tol= 0.02
Split Flow Ratio= 0.02
Log Output Level= 0
Friction Slope Method= 1
Unsteady Friction Slope Method= 2
Unsteady Bridges Friction Slope Method= 1
Parabolic Critical Depth
Global Vel Dist= 0 , 0 , 0
Global Log Level= 0
CheckData=True
Encroach Param=-1 ,0,0, 0
Mapping Interval=1HOUR
Computation Time Step Use Courant=        0
Computation Time Step Use Time Series=    0
Computation Time Step Count To Double=0
Computation Time Step Max Doubling=0
Computation Time Step Max Halving=0
Computation Time Step Residence Courant=0
Run HTab= 0
Run UNet= 0
Run Sediment= 0
Run PostProcess= 0
Run WQNet= 0
Run RASMapper=-1
UNET Theta= 0
UNET Theta Warmup= 0
UNET ZTol= 0
UNET ZSATol= 0
UNET MxIter= 0
UNET Max Iter WO Improvement= 0
UNET MaxInSteps= 0
UNET DtIC= 0
UNET DtMin= 0
UNET MaxCRTS= 0
UNET WFStab= 0
UNET SFStab= 0
UNET WFX= 1
UNET SFX= 1
UNET Gravity=32.174
UNET 1D Methodology=Finite Difference
UNET DSS MLevel= 1
UNET Pardiso=0
UNET DZMax Abort= 0
UNET Use Existing IB Tables= 0
UNET Froude Reduction=False
UNET Froude Limit= 0
UNET Froude Power= 0
UNET D1 Cores= 0
UNET WindReference=Eulerian
UNET WindDragFormulation=Hsu (1988)
UNET D2 Coriolis=0
UNET D2 Cores= 0
UNET D2 Theta= 1
UNET D2 Theta Warmup= 1
UNET D2 Z Tol= 0.01
UNET D2 Volume Tol= 0.01
UNET D2 Max Iterations= 20
UNET D2 Equation= 0
UNET D2 RampUpFraction=0.1
UNET D2 TimeSlices= 1
UNET D2 Turbulence Formulation=Non-Conservative (original)
UNET D2 Eddy Viscosity=0.3
UNET D2 Transverse Eddy Viscosity=0.1
UNET D2 Smagorinsky Mixing=0
UNET D2 BCVolumeCheck=0
UNET D2 Cores=0
UNET D2 SolverType=PARDISO (Direct)
UNET D2 Minimum Iterations= 2147483647
UNET D2 Maximum Iterations= 2147483647
UNET D2 Restart Number= 10
UNET D2 Relaxation Coeff=1.3
UNET D2 SOR Precondition Iterations= 10
UNET D2 ILUT Maximum Fill= 8
UNET D2 ILUT Tolerance=1E-08
UNET D1D2 MaxIter= 0
UNET D1D2 ZTol=0.01
UNET D1D2 QTol=0.1
UNET D1D2 MinQTol=1
Write IC File= 0
Write IC File at Fixed DateTime=0
Write IC File at Sim End=0
Echo Input=False
Echo Parameters=False
Echo Output=False
Write Detailed= 0
HDF Write Warmup=0
HDF Write Time Slices=0
HDF Flush=0
HDF Compression= 1
HDF Chunk Size= 1
HDF Spatial Parts= 1
HDF Use Max Rows=0
HDF Fixed Rows= 1
Calibration Method= 0
Calibration Iterations= 20
Calibration Max Change=0.05
Calibration Tolerance=0.2
Calibration Maximum=1.5
Calibration Minimum=0.5
Calibration Optimization Method= 1
WQ AD Non Conservative
WQ ULTIMATE=-1
WQ Max Comp Step=1HOUR
WQ Output Interval=15MIN
WQ Output Selected Increments= 0
WQ Output face flow=0
WQ Output face velocity=0
WQ Output face area=0
WQ Output face dispersion=0
WQ Output cell volume=0
WQ Output cell surface area=0
WQ Output cell continuity=0
WQ Output cumulative cell continuity=0
WQ Output face conc=0
WQ Output face dconc_dx=0
WQ Output face courant=0
WQ Output face peclet=0
WQ Output face adv mass=0
WQ Output face disp mass=0
WQ Output cell mass=0
WQ Output cell source sink temp=0
WQ Output nsm pathways=0
WQ Output nsm derived pathways=0
WQ Create Restart=0
WQ Fixed Restart=0
WQ System Summary=0
WQ Write To DSS=0
Sorting and Armoring Iterations= 10
XS Update Threshold= 0.02
Bed Roughness Predictor= 0
Hydraulics Update Threshold= 0.02
Energy Slope Method= 1
Volume Change Method= 1
Sediment Retention Method= 0
Sediment TS Multiplier= 1
Warm Up Method= 0
XS Weighting Method= 0
Number of US Weighted Cross Sections= 1
Number of DS Weighted Cross Sections= 1
Upstream XS Weight=0
Main XS Weight=1
Downstream XS Weight=0
Number of DS XS's Weighted with US Boundary= 1
Upstream Boundary Weight= 1
Weight of XSs Associated with US Boundary= 0
Number of US XS's Weighted with DS Boundary= 1
Downstream Boundary Weight= 0.5
Weight of XSs Associated with DS Boundary= 0.5
Percentile Method= 0
Sediment Output Level= 3
Mass or Volume Output= 0
Output Increment Type= 1
Profile and TS Output Increment= 1
Transport Output Increment 1
XS Output Flag= 0
XS Output Increment= 10
Read HDF5 Sediment Hotstart= 0
Sediment Hotstart Type= 0
Write Gradation File= 0
Read Gradation Hotstart= 0
Write HDF5 File= 1
Write Binary Output= 1
Write DSS Sediment File= 0
DSS Sediment Output Type= 1
SV Curve= 0
Specific Gage Flag= 0
Subcell Erosion Methods= 0
Subcell Deposition Methods= 0
Advection Scheme= 1
Matrix Solver= 0
Implicit Weighting Factor= 1
Maximum Outer Loop Convergence Iterations= 5
Convergence Maximum Absolute= 0.001
Convergence RMSE= 0.0001
Grain Fractions Max Abs Error= 0.001
Max Subgrid Regions= 1
Max Subgrid Length Scale= 3.402823E+38
Initial Layer Thickness= 3.402823E+38
Min Layer Thickness= 3.402823E+38
Max Layer Thickness= 3.402823E+38
Number of Layers= 5

--- MARSHFK.f01 (steady flow) ---

Flow Title=Flow
Program Version=6.20
Number of Profiles= 1
Profile Names=P100yr
River Rch & RM=MARSHFK,Main            ,19393
     393
River Rch & RM=MARSHFK,Main            ,15306
     463
River Rch & RM=MARSHFK,Main            ,15119
     517
River Rch & RM=MARSHFK,Main            ,12497
     611
River Rch & RM=MARSHFK,Main            ,8564
     680
River Rch & RM=MARSHFK,Main            ,5488
     928
River Rch & RM=MARSHFK,Main            ,320
    1870
Boundary for River Rch & Prof#=MARSHFK,Main            , 1
Up Type= 0
Dn Type= 1
Dn Known WS=2394.3
DSS Import GetInterval= 0
DSS Import GetPeak= 0
DSS Import FillOption= 0

--- MARSHFK.g01 (geometry) ---

Geom Title=Geometry
Program Version=6.20

River Reach=MARSHFK         ,Main
Reach XY= 30
2189297.23799999601632.1040000172189159.51000004602123.998000011
     2189492.424602221.8720000092189771.05500004602737.279000014
2189679.37692831603035.6642968512189491.66300003603044.285000011
2189487.71500002604268.9170000112189118.27800001      604316.272
2188914.71900001604672.6090000122189129.99600002605321.047000006
2188833.12200001 605529.81400001     2188803.608605756.377000034
     2187739.692606418.350000009     2188063.947606941.958000004
     2187596.543607809.3959999982187075.70900004608271.359999999
2185454.06943546608603.7058202482184745.94900003609194.827000022
2184609.74699999609686.9940000032184306.35199998610085.584000021
2183900.91900003610241.5160000032183714.72800003610658.104000002
2183913.72138339610919.2395528852184009.57216428611621.262880385
     2183550.786612009.3100000172183535.35700001612392.636999995
     2184107.838612666.9400000132184414.05600002613305.156000003
2185433.62300003613646.2720000152185518.00250443614227.228011066

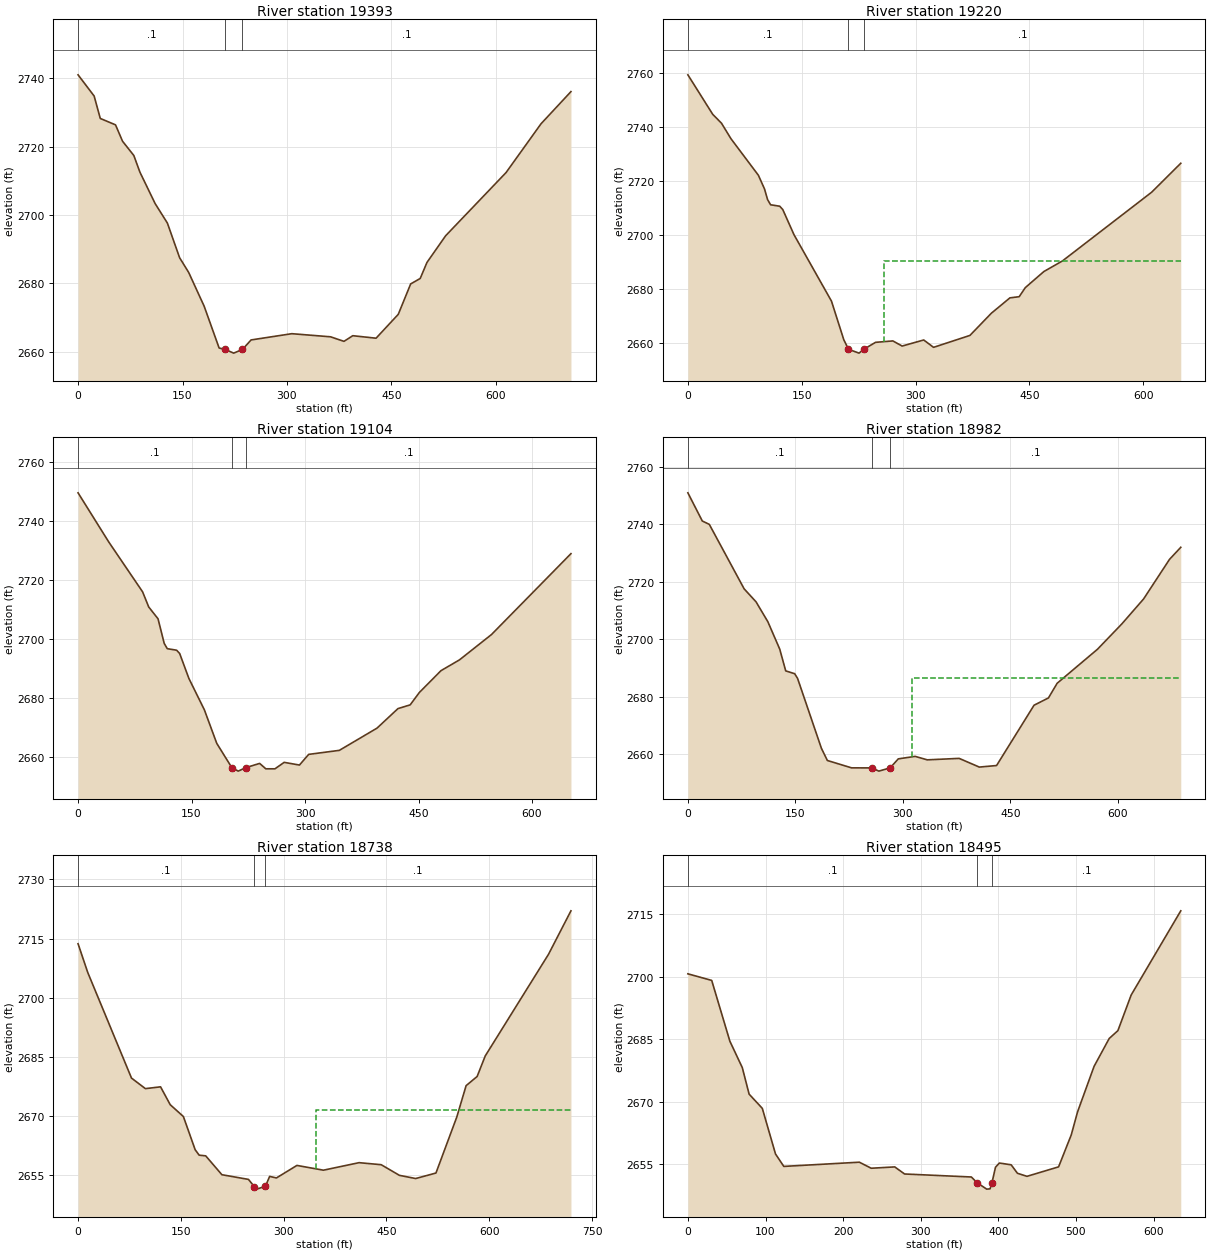
Type RM Length L Ch R = 1 ,19393   ,174.1,173.6,172.2
XS GIS Cut Line= 4
2189091.03937773601707.2222247192189274.23450315601625.520793601
2189497.02491099601691.9352525252189737.93688619601824.298731702
#Sta/Elev= 30
       0 2741.04    23.1 2734.83    31.9 2728.27    53.8 2726.39    63.9 2721.59
    80.1 2717.42    88.8 2712.56   110.7 2703.34   128.3 2697.63   145.8 2687.51
   158.9 2683.17   181.1 2673.29   202.6 2661.05  211.57 2660.62   223.5 2659.55
  236.052660.621   248.5 2663.41     307 2665.24   362.6 2664.33   381.9    2663
   394.6 2664.65     428 2663.92   459.9 2670.91   477.7 2679.81   491.4 2681.41
   501.1  2686.1   527.9 2693.91   614.7 2712.42   664.9  2726.7   707.9 2736.12
#Mann= 3 ,-1,0
       0      .1       0  211.57    .045       0  236.05      .1       0
Bank Sta=211.57,236.05
XS Rating Curve= 0 ,0
Exp/Cntr=0.3,0.1

Type RM Length L Ch R = 1 ,19220   ,118,115.3,112
XS GIS Cut Line= 4
 2189039.5108246601781.3250931292189244.33747823601796.842263859
2189383.21615627601820.1180199532189681.92169281601872.100541897
#Sta/Elev= 30
       0 2759.25    32.8 2744.63    44.3 2741.37    56.8 2735.63    92.9 2722.14
     101 2717.06     105 2713.15     109 2711.23     121  2710.7     125 2709.48
   139.8 2700.19   189.2 2675.63   205.4 2661.39  211.622657.837   225.5 2656.42
  231.782657.835   247.2  2660.4   270.1 2660.93   282.3 2659.03   310.7 2661.28
   323.7 2658.56   371.6 2662.96   399.8 2671.15   424.3 2676.84   436.5 2677.27
   444.6 2680.63     469 2686.56   493.6  2690.5   611.1 2715.89   649.4 2726.57
#Mann= 3 ,-1,0
       0      .1       0  211.62    .045       0  231.78      .1       0
#XS Ineff= 2 , 0
                          258.27         2690.28
Permanent Ineff=
       F       F
Bank Sta=211.62,231.78
XS Rating Curve= 0 ,0
Exp/Cntr(USF)=0,0
Exp/Cntr=0.3,0.1

Type RM Length L Ch R = 1 ,19104   ,116.8,123,129.5
XS GIS Cut Line= 4
2189040.62667163601878.4659745052189227.93956932601916.779976306
2189398.92229446601890.1730306112189680.71751928601945.357806868
#Sta/Elev= 30
       0 2749.58    40.4 2732.95    85.3 2715.95    93.4 2710.81   105.7 2706.79
   113.9 2698.42   117.9 2696.65   130.2 2696.13   134.3    2695   146.5 2686.52
   166.9  2675.9   183.3  2664.5  203.172656.253   211.7 2655.06  221.772656.247
     240 2657.68   248.1 2655.85   260.2 2655.84   272.4 2658.04   292.6 2657.12
   304.8 2660.75   345.3 2662.11   395.1 2669.66   422.8  2676.3   438.9 2677.56
   451.1 2681.78   479.6 2689.17   504.1 2692.85   546.4 2701.45   651.4 2728.92
#Mann= 3 ,-1,0
       0      .1       0  203.17    .045       0  221.77      .1       0
Bank Sta=203.17,221.77
XS Rating Curve= 0 ,0
Exp/Cntr(USF)=0,0
Exp/Cntr=0.3,0.1

Type RM Length L Ch R = 1 ,18982   ,244.9,243.4,229
XS GIS Cut Line= 4
 2189012.5039099601956.1507941492189198.75252977602007.236129884
2189337.10864739602054.0643543082189683.85378598602018.674371217
#Sta/Elev= 30
       0 2750.96    20.1 2741.15    29.9 2739.97    78.5 2717.51    95.1 2712.99
   111.6 2706.05   128.2 2696.49   136.5 2688.93     149 2687.95   153.1 2686.29
   186.3 2661.97   194.6 2657.72   228.4 2655.15  256.732655.134   266.4 2654.01
  282.142655.134   293.6 2658.28   317.1 2659.15     334 2657.94   378.5 2658.45
   406.6 2655.42   430.7 2655.96     483 2676.97   503.1 2679.51   515.2 2684.61
   571.5 2696.47   605.5  2705.3   635.8 2713.98     672 2727.78   687.7 2731.98
#Mann= 3 ,-1,0
       0      .1       0  256.73    .045       0  282.14      .1       0
#XS Ineff= 2 , 0
                          313.36         2686.34
Permanent Ineff=
       F       F
Bank Sta=256.73,282.14
XS Rating Curve= 0 ,0
Exp/Cntr(USF)=0,0
Exp/Cntr=0.3,0.1

Type RM Length L Ch R = 1 ,18738   ,246.8,243.3,231.8
XS GIS Cut Line= 4
2189002.01972825 602298.433988632189179.88897344602187.625191575
2189295.53594086602102.0808603672189660.88316144602082.689456512
#Sta/Elev= 30
       0 2713.68    14.1  2706.4      78 2679.56    98.3 2676.88   120.4 2677.34
   134.5  2672.8   153.7  2669.8   170.9 2661.37   176.7 2659.99   186.3 2659.81
   209.9 2655.02   248.7 2653.83   257.3 2651.98   260.8 2651.36 273.4982652.102
   279.6 2654.59   289.5  2654.2   319.4 2657.38   358.1 2656.17   410.1 2658.08
   442.4 2657.56     469 2654.86   492.7 2654.05   522.3 2655.45   552.7 2669.67
   566.3 2677.64   582.4 2679.97   594.2 2685.18   686.5 2710.98   719.3 2722.04
#Mann= 3 ,-1,0
       0      .1       0   257.3    .045       0 273.498      .1       0
#XS Ineff= 2 , 0
                          346.57         2671.38
Permanent Ineff=
       F       F
Bank Sta=257.3,273.498
XS Rating Curve= 0 ,0
Exp/Cntr(USF)=0,0
Exp/Cntr=0.3,0.1

Type RM Length L Ch R = 1 ,18495   ,105.1,112.4,120.7
XS GIS Cut Line= 5
  2189133.369388 602425.690158862189215.31878074 602333.09798784
2189411.09375145602195.4420905352189412.35064228602162.134483563
 2189646.7607819602116.886413716
#Sta/Elev= 30
       0 2700.68    30.7  2699.1    54.1 2684.52    70.1 2678.19    78.9 2671.82
    95.9 2668.41   112.9 2657.47   123.6 2654.49   220.9  2655.5   236.2 2654.05
   266.5 2654.37   279.2 2652.67   365.2 2651.95  372.662650.555     385 2649.04
   389.3  2649.1  391.752650.554   396.3 2654.29   401.3  2655.3   416.5 2654.87
   424.6 2652.84   436.9 2652.11   477.6 2654.38   493.9 2662.04     502 2667.55
   523.3 2678.48   542.8 2685.17     554 2687.05   571.1  2695.6     635 2715.79
#Mann= 3 ,-1,0
       0      .1       0  372.66    .045       0  391.75      .1       0
Bank Sta=372.66,391.75
XS Rating Curve= 0 ,0
Exp/Cntr(USF)=0,0
Exp/Cntr=0.3,0.1

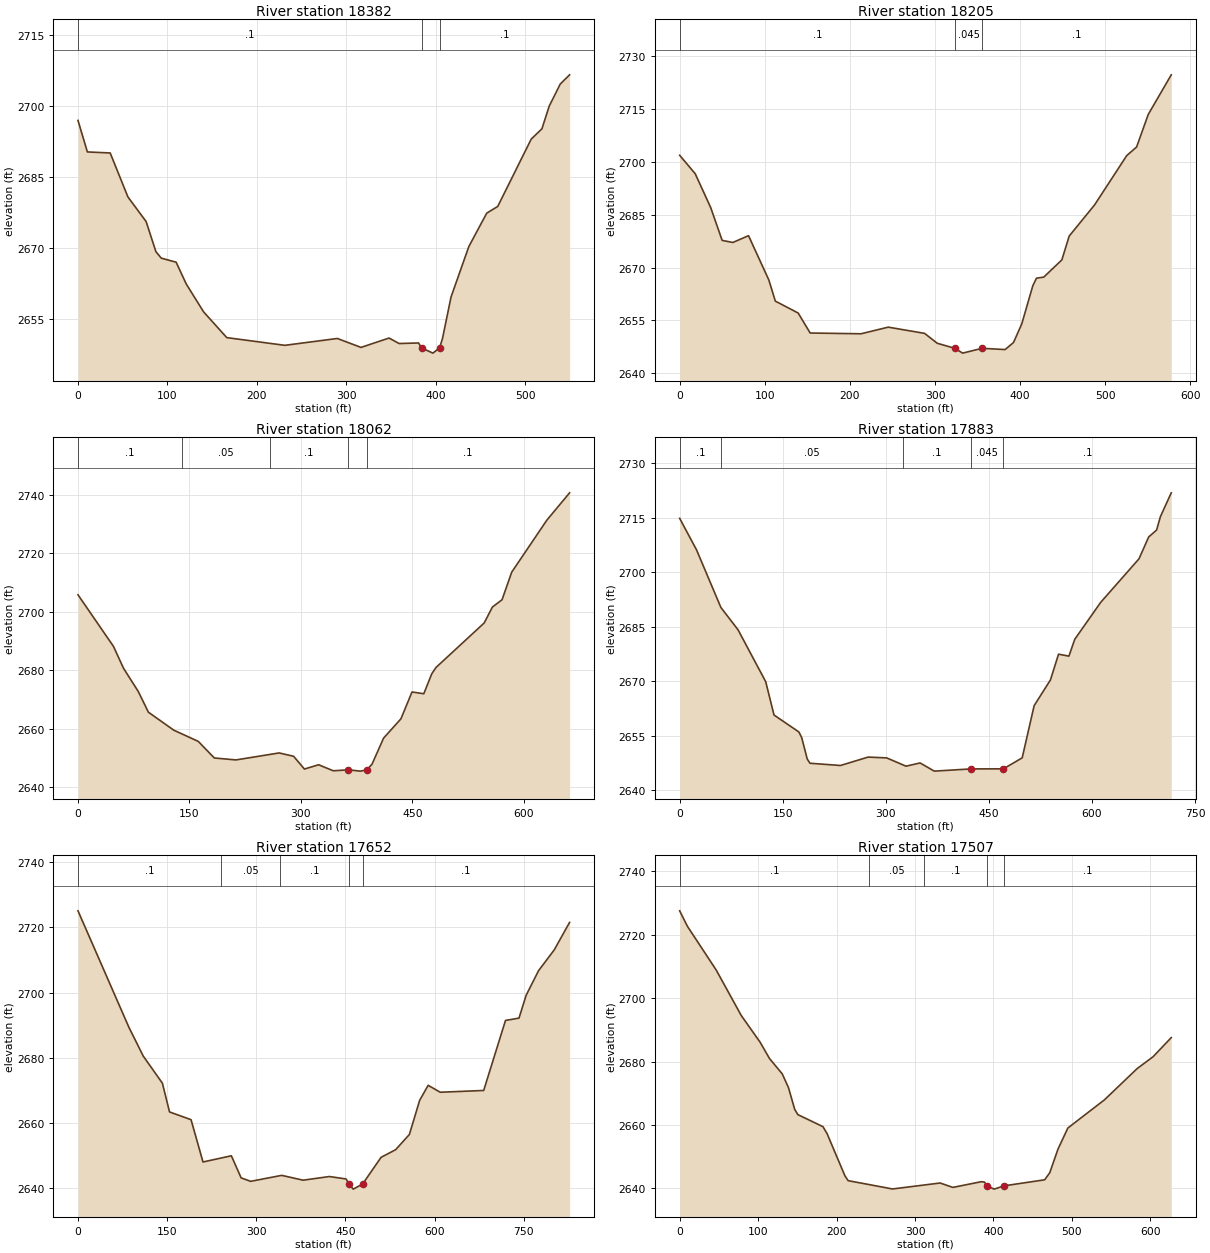
Type RM Length L Ch R = 1 ,18382   ,177.6,177,173.5
XS GIS Cut Line= 4
 2189207.2023951602495.0219268452189328.89463025602386.950411897
2189512.53887805602224.6075560992189650.26759012602191.570335297
#Sta/Elev= 30
       0 2696.95    10.5 2690.29      36 2690.07    55.8 2680.77    76.2 2675.55
    87.1 2669.19    93.1 2667.82   109.7 2666.97     121 2662.36   140.4 2656.46
   166.3 2651.01   231.2 2649.38   289.9 2650.83   316.4 2648.94   347.7 2650.92
     359 2649.76   380.7 2649.88  384.012648.839   396.7 2647.73  404.16 2648.84
   407.4 2650.78     417 2659.61   436.9 2670.28   456.9 2677.34   469.2 2678.76
   506.6    2693   518.6 2695.19   526.8 2700.01   539.1 2704.66   549.5  2706.6
#Mann= 3 ,-1,0
       0      .1       0  384.01    .045       0  404.16      .1       0
Bank Sta=384.01,404.16
XS Rating Curve= 0 ,0
Exp/Cntr=0.3,0.1

Type RM Length L Ch R = 1 ,18205   ,141.3,143.7,142.9
XS GIS Cut Line= 4
2189251.47661718602580.9567396362189382.38279001602516.035792138
2189587.91825267 602363.844062762189752.71060582602303.094339354
#Sta/Elev= 30
       0  2701.8    18.3 2696.56    36.5 2686.96    49.9 2677.69    62.5  2677.1
    80.9 2679.02   104.8 2666.45   112.4 2660.48   139.2 2657.11   153.3 2651.45
   213.1 2651.23     245 2653.11   287.7 2651.35   302.6 2648.54  323.32 2647.11
   332.4 2645.75   355.3 2647.11   382.3 2646.76   392.2 2648.76   401.9 2654.04
   414.9 2664.86   419.2 2666.99   427.7 2667.28     449 2672.17   457.6 2678.91
   487.4 2687.73   525.2 2701.71   536.8 2704.15   550.5 2713.38   577.5 2724.59
#Mann= 3 ,-1,0
       0      .1       0  323.32    .045       0   355.3      .1       0
Bank Sta=323.32,355.3
XS Rating Curve= 0 ,0
Exp/Cntr(USF)=0,0
Exp/Cntr=0.3,0.1

Type RM Length L Ch R = 1 ,18062   ,181.7,179,178.8
XS GIS Cut Line= 4
2189285.64701054602672.3505806522189455.93146299 602619.13668926
2189648.56574983 602487.16623861 2189880.5783163602394.574067589
#Sta/Elev= 30
       0 2705.86    47.8  2688.2    61.3 2680.72    81.2 2672.77    94.8  2665.7
   129.1 2659.54   161.9 2655.72   183.5 2650.05   212.6 2649.38   270.8 2651.77
   290.2 2650.63   304.8 2646.26   323.9 2647.73   343.6 2645.67   364.1 2645.99
     380 2645.55  388.862645.991   395.8 2647.94   411.4 2656.86   434.7 2663.44
   449.6 2672.62   465.5 2672.02   476.1  2678.8     482 2681.03   546.8 2696.24
   557.8 2701.67   570.8 2704.17   583.8  2713.6   631.1 2731.39   661.7 2740.74
#Mann= 5 ,-1,0
       0      .1       0     140     .05       0  258.41      .1       0
   364.1    .045       0  388.86      .1       0
Bank Sta=364.1,388.86
XS Rating Curve= 0 ,0
Exp/Cntr(USF)=0,0
Exp/Cntr=0.3,0.1

Type RM Length L Ch R = 1 ,17883   ,204.1,230.9,234.5
XS GIS Cut Line= 4
2189295.86473028602775.5712244242189608.63605101602738.289398539
2189759.64772536602626.099819515 2189902.7801032602469.387837087
#Sta/Elev= 30
       0 2714.83    24.5 2706.18      60 2690.31    84.9 2684.19   125.2  2669.9
   137.3 2660.73   173.5 2656.07   177.6 2654.51   185.6 2648.65   189.6 2647.47
     234 2646.85   274.2 2649.16   301.2 2648.94   329.4 2646.66   349.8 2647.55
   370.5  2645.3     424 2645.91   471.1 2645.93   498.4 2648.95   515.8 2663.31
   539.5 2670.38   551.3 2677.47   566.4 2676.93   574.9 2681.57   612.7 2691.74
   668.4 2703.71   682.5 2709.72     694 2711.62   699.5 2715.29   715.3 2721.85
#Mann= 5 ,-1,0
       0      .1       0      60     .05       0  324.99      .1       0
     424    .045       0   471.1      .1       0
Bank Sta=424,471.1
XS Rating Curve= 0 ,0
Exp/Cntr=0.3,0.1

Type RM Length L Ch R = 1 ,17652   ,141.6,145.1,143.9
XS GIS Cut Line= 4
2189282.84288307602866.2265730992189492.15085588602846.123547462
 2189784.2848316602867.6022113182190017.90682264603091.838927468
#Sta/Elev= 30
       0 2725.07    85.7 2689.35   109.8 2680.54     142 2672.23     154 2663.42
   190.2 2661.05   210.3 2648.08     258 2649.98   274.5  2643.2   290.5 2642.15
   342.7 2643.98   378.7  2642.5   422.9 2643.62   450.9 2642.88  456.142641.311
     463 2639.76  478.792641.313   509.9 2649.51   534.4 2651.85   557.5 2656.51
   574.8 2666.98   589.1 2671.58   609.4 2669.46   682.5    2670   719.2 2691.47
   741.9 2692.18   753.9 2699.16   774.7 2706.69   801.3 2713.13     827 2721.52
#Mann= 5 ,-1,0
       0      .1       0  240.27     .05       0  340.27      .1       0
  456.14    .045       0  478.79      .1       0
Bank Sta=456.14,478.79
XS Rating Curve= 0 ,0
Exp/Cntr(USF)=0,0
Exp/Cntr=0.3,0.1

Type RM Length L Ch R = 1 ,17507   ,292.6,290,289
XS GIS Cut Line= 4
 2189277.6754818602941.283989429 2189489.3631156 602951.50339244
2189746.26951829602990.4792566232189866.02111228603088.735375726
#Sta/Elev= 30
       0 2727.54     9.9 2722.65    46.6 2708.86    78.5 2694.52   102.6 2686.08
   114.6 2680.92   130.7 2676.13   138.7 2671.79   146.7 2664.88   150.7 2663.25
   182.7 2659.45   187.9 2657.27   210.7 2643.94   214.8 2642.42   271.4  2639.8
   332.1 2641.68   348.3 2640.29   384.7  2642.1   388.7 2641.96   391.5 2640.84
   400.9 2639.75   413.6 2640.79   465.3 2642.69   471.8 2644.92   482.3 2652.37
   494.9 2659.03   541.5 2667.91   583.2 2677.77   603.6 2681.53   626.7 2687.55
#Mann= 5 ,-1,0
       0      .1       0  241.93     .05       0  311.93      .1       0
   391.5    .045       0   413.6      .1       0
Bank Sta=391.5,413.6
XS Rating Curve= 0 ,0
Exp/Cntr(USF)=0,0
Exp/Cntr=0.3,0.1

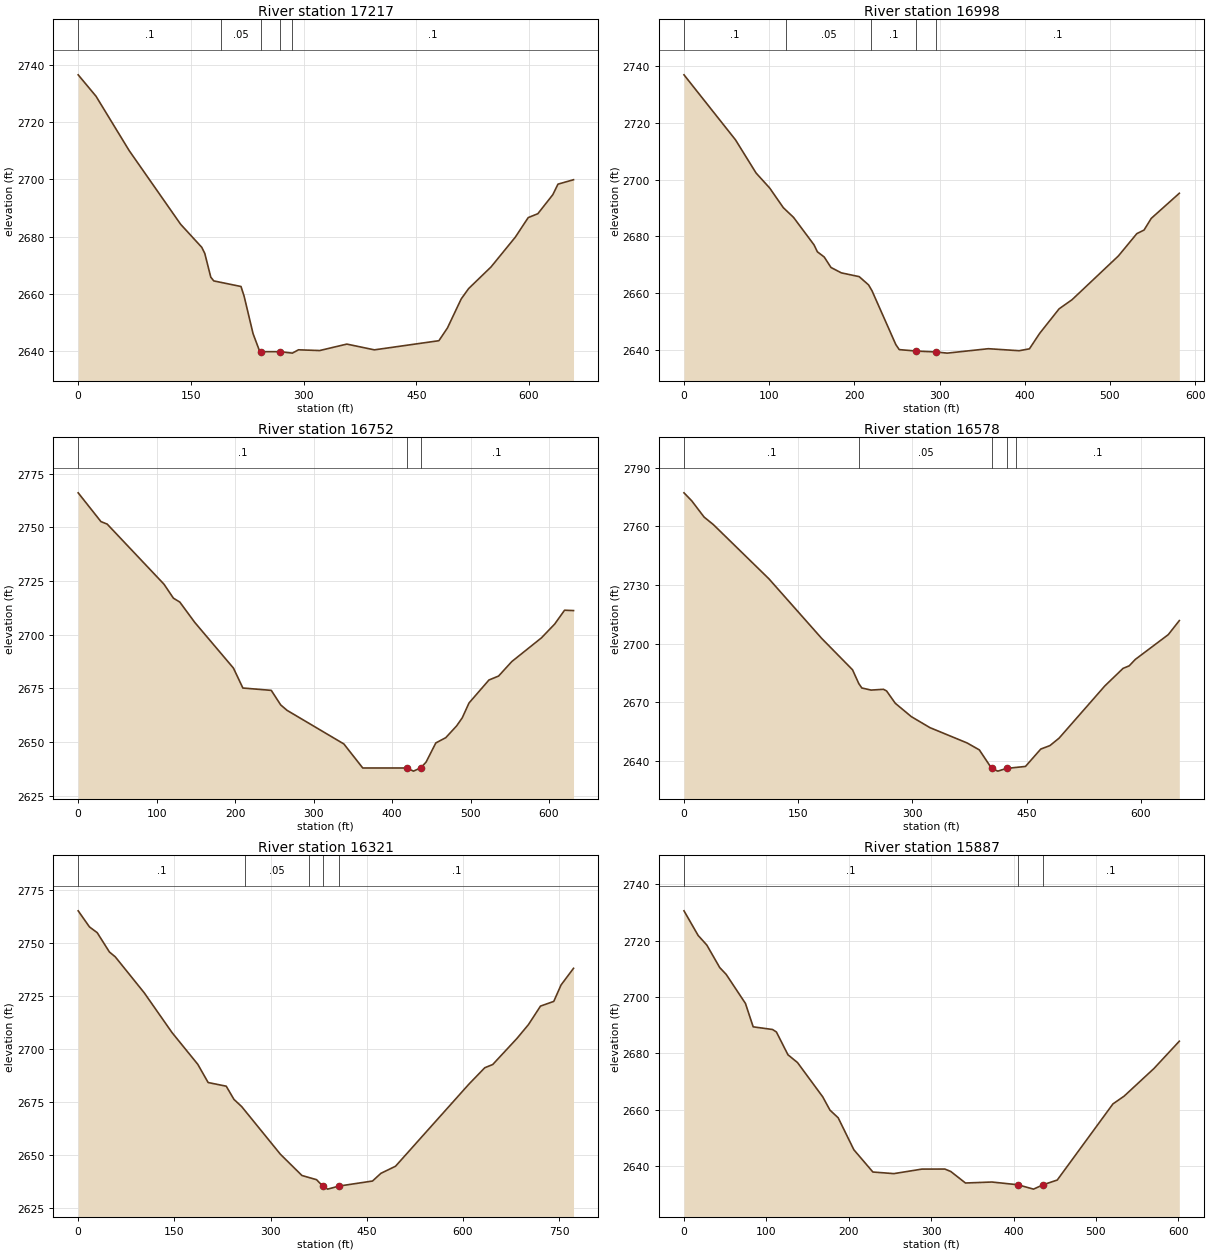
Type RM Length L Ch R = 1 ,17217   ,215,218.4,215.4
XS GIS Cut Line= 4
2189236.56259427603010.0872786922189469.84746165603033.911931597
2189597.97096724603048.3716950422189836.86502515603222.927225989
#Sta/Elev= 30
       0 2736.43    23.7 2728.98      68 2709.96   136.3 2684.34   164.5 2676.28
   168.5 2674.17   176.5 2665.87   180.5 2664.57   216.7 2662.62   220.8  2659.3
   232.8 2646.15   240.9 2640.49243.60412639.899   268.5  2639.9   285.1 2639.39
   293.2 2640.55   321.4 2640.29   357.6 2642.54   394.2 2640.53   480.1 2643.72
   491.5 2648.17   509.8 2658.28   519.7  2661.9   549.5 2669.44   581.8 2679.82
     599 2686.65   611.8    2688   631.8 2694.66   638.6 2698.31   659.3 2699.85
#Mann= 5 ,-1,0
       0      .1       0     190     .05       0243.6041    .045       0
   268.5     .05       0   284.5      .1       0
Bank Sta=243.6041,268.5
XS Rating Curve= 0 ,0
Exp/Cntr(USF)=0,0
Exp/Cntr=0.3,0.1

Type RM Length L Ch R = 1 ,16998   ,247.3,246.5,245.7
XS GIS Cut Line= 4
2189207.68311762603224.978603653 2189455.6820525603214.367939389
2189624.95762594603231.7244967952189779.42943353603284.199162012
#Sta/Elev= 30
       0 2736.96    60.5 2714.02    84.6 2702.34   100.6 2697.04   116.6 2690.11
   128.6 2686.69   152.6 2677.02   156.6 2674.55   164.6 2672.71   172.6 2669.01
   184.7 2667.12   205.7 2665.78   216.7 2662.87   220.7 2660.82   248.7 2641.82
   252.7 2640.05   272.8 2639.54     296 2639.22     309 2638.81   357.3 2640.37
   393.4 2639.66   405.5 2640.32   417.6  2645.8   440.4 2654.44   455.6 2657.66
     510 2673.09   531.6 2680.95   540.1 2682.22   548.5 2686.32   581.5 2695.19
#Mann= 5 ,-1,0
       0      .1       0     120     .05       0     220      .1       0
   272.8    .045       0     296      .1       0
Bank Sta=272.8,296
XS Rating Curve= 0 ,0
Exp/Cntr=0.3,0.1

Type RM Length L Ch R = 1 ,16752   ,173.3,173.8,172.7
XS GIS Cut Line= 4
2189139.36713748603405.0756352852189497.67400618603441.734093799
2189585.18129425603453.5594029982189759.01333946603510.320887149
#Sta/Elev= 30
       0 2766.08      29 2752.68      37  2751.5   109.4 2723.49   121.4 2716.99
   129.5 2715.19   148.6  2705.7   197.9 2684.41   209.9 2675.14   246.1 2674.04
   258.1 2667.27   266.2 2664.74   338.6 2649.08   362.7 2637.88   418.8 2637.88
   427.3 2636.42  436.752637.968   443.4 2640.64   455.8 2649.55   468.5 2652.01
   482.3 2657.49   489.5 2661.26   498.1 2668.16   523.5 2678.87   535.8 2680.72
   552.6 2687.45   590.5 2698.54   607.3 2704.94   619.9 2711.39   631.3 2711.22
#Mann= 3 ,-1,0
       0      .1       0   418.8    .045       0  436.75      .1       0
Bank Sta=418.8,436.75
XS Rating Curve= 0 ,0
Exp/Cntr(USF)=0,0
Exp/Cntr=0.3,0.1

Type RM Length L Ch R = 1 ,16578   ,257.7,257.1,255.8
XS GIS Cut Line= 4
2189094.15346034603534.1616902332189484.38866387603602.485698933
2189543.51520987603610.3692383992189737.97585001 603616.93885462
#Sta/Elev= 30
       0 2777.08    10.2 2772.98    26.4 2764.69    38.6 2760.83   111.5 2733.13
   180.7  2702.7   221.3 2686.62   229.5 2679.58   233.5 2677.32   245.7 2676.24
   261.9 2676.64     266  2675.8   277.4 2669.51   298.5 2662.67   322.9 2657.05
   371.6 2649.24   387.8 2645.67  404.012636.197   412.1 2634.81  423.492636.198
   448.4 2637.21   468.5  2646.1   480.5 2647.86   492.5 2651.66   552.5 2678.33
   576.5 2687.33   584.6 2688.64   592.6 2691.92   635.9 2704.59   650.4 2711.77
#Mann= 5 ,-1,0
       0      .1       0     230     .05       0  404.01    .045       0
  423.49     .05       0  436.17      .1       0
Bank Sta=404.01,423.49
XS Rating Curve= 0 ,0
Exp/Cntr(USF)=0,0
Exp/Cntr=0.3,0.1

Type RM Length L Ch R = 1 ,16321   ,420.3,433.4,440.1
XS GIS Cut Line= 4
2189070.70095318603812.8034715822189446.82880976603855.075834138
2189523.06880071603861.1130962352189829.94268294603778.987560986
#Sta/Elev= 30
       0 2765.23    17.6 2757.63    29.7  2754.9    48.7 2745.78    57.8  2743.5
     103 2726.49   146.4 2707.68   186.6 2692.67   202.7 2684.07   230.9 2682.35
     243  2676.1     255 2672.71   315.4 2650.18     349 2640.13   371.8 2638.15
  381.382635.151   389.1 2633.69  407.042635.149   459.1 2637.52   472.2 2641.16
     495 2644.51   609.3 2683.27   634.2 2691.07   646.6 2692.59   684.5 2704.96
   702.3 2711.45   721.1  2720.2   741.8 2722.42   753.1 2730.16   772.6 2738.06
#Mann= 5 ,-1,0
       0      .1       0     260     .05       0     360      .1       0
  381.38    .045       0  407.04      .1       0
Bank Sta=381.38,407.04
XS Rating Curve= 0 ,0
Exp/Cntr=0.3,0.1

Type RM Length L Ch R = 1 ,15887   ,205,219.3,234.1
XS GIS Cut Line= 4
2189144.56170468604029.1418149562189334.65267953604145.741011409
2189514.24121138604307.5322764192189577.69426521604428.515107707
#Sta/Elev= 30
       0 2730.59    17.2 2721.85    27.7 2718.46    43.4 2710.46    51.2 2708.06
    74.6 2697.75      84 2689.45   107.5  2688.5   112.2 2687.62   126.2 2679.54
   137.8 2676.78   168.4 2664.63   177.2 2659.91   187.2 2657.18   206.2 2645.86
   229.3 2637.96   254.8 2637.39   288.8 2638.99   316.6 2639.01   323.8 2638.16
   341.7 2634.06   373.8 2634.41  405.322633.436   424.3 2631.89  435.992633.437
   453.1 2635.11   520.7 2662.11   534.3 2664.87   570.5 2674.67   601.3 2684.35
#Mann= 3 ,-1,0
       0      .1       0  405.32    .045       0  435.99      .1       0
Bank Sta=405.32,435.99
XS Rating Curve= 0 ,0
Exp/Cntr=0.3,0.1

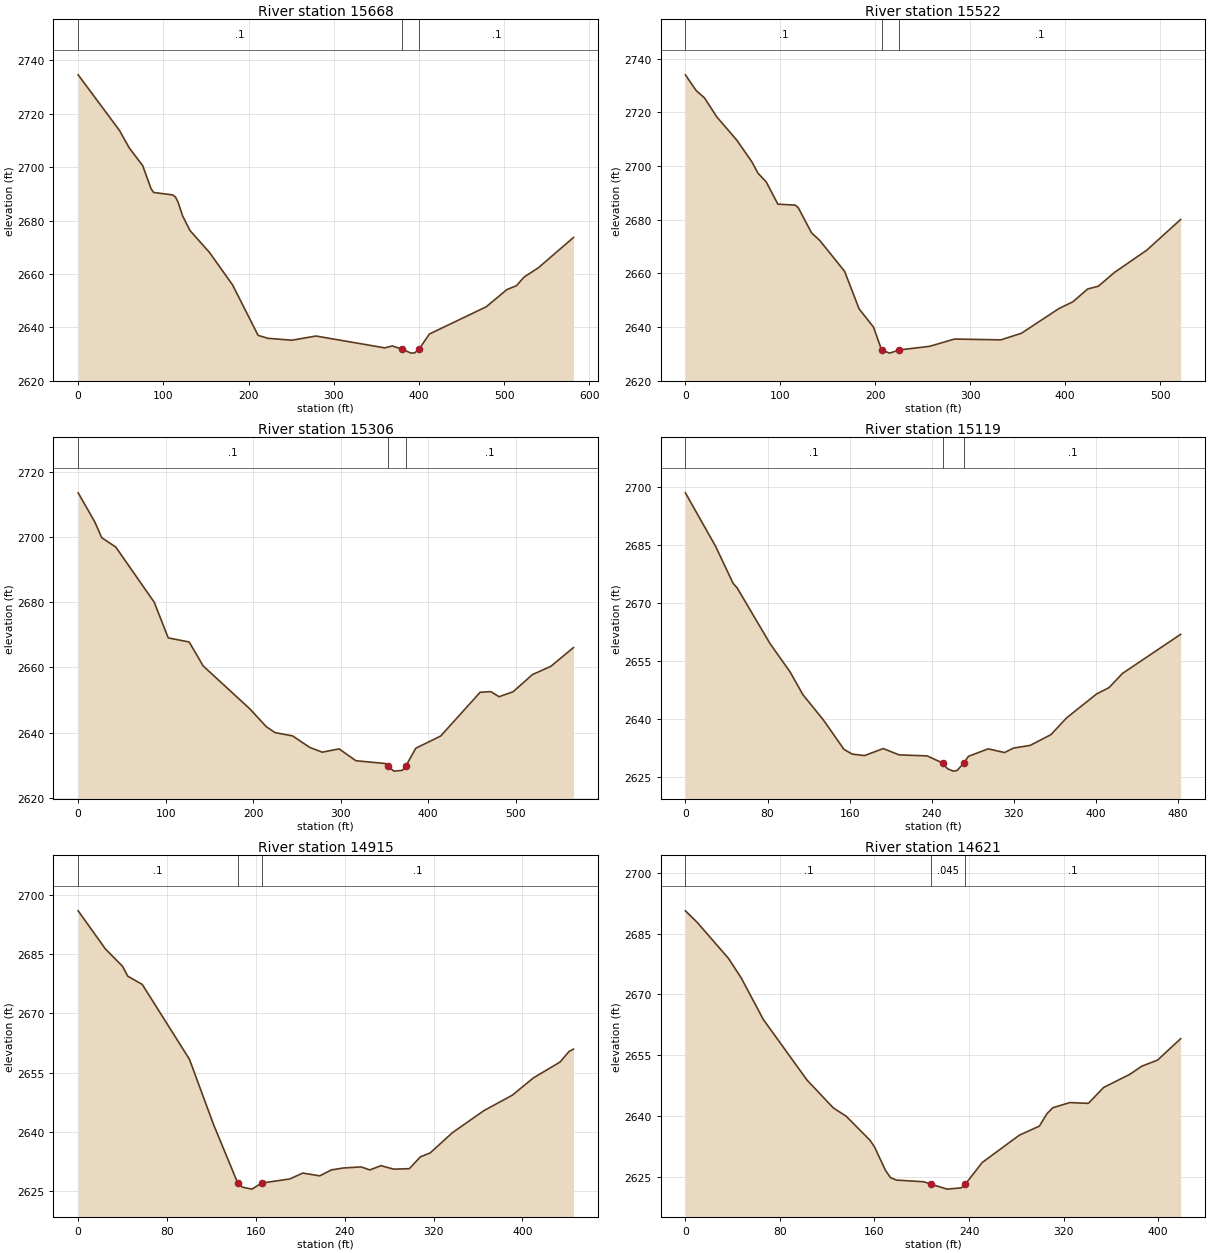
Type RM Length L Ch R = 1 ,15668   ,152.9,146.1,135.3
XS GIS Cut Line= 4
2189111.85153333604065.525124566 2189330.2413436604231.233182359
 2189272.7703409604356.7115382612189377.17599581604489.852694523
#Sta/Elev= 30
       0 2734.61    48.5 2713.76    59.9 2707.24    75.7  2700.6    85.6 2691.89
    88.5 2690.53   110.9 2689.61   114.2 2688.82     117 2687.08   122.7 2681.66
   131.3 2676.24   154.1 2668.06   181.2 2655.88   211.2 2636.97   222.7 2635.87
   250.9 2635.15   279.1 2636.72   359.9 2632.28   368.7    2633   379.8 2631.83
   390.7 2630.31   395.1 2630.43  400.262631.884   412.2 2637.46   478.8 2647.65
   503.2 2654.13   514.4 2655.58   523.2 2658.77   540.3 2662.34   581.3 2673.64
#Mann= 3 ,-1,0
       0      .1       0   379.8    .045       0  400.26      .1       0
Bank Sta=379.8,400.26
XS Rating Curve= 0 ,0
Exp/Cntr(USF)=0,0
Exp/Cntr=0.3,0.1

Type RM Length L Ch R = 1 ,15522   ,219.2,216,210.8
XS GIS Cut Line= 4
2189063.24988561 604102.632571742189139.48987633604284.310847487
2189199.50859242604392.9933874422189334.56544877604541.012307475
#Sta/Elev= 30
       0    2734    11.4 2728.11    20.1 2725.42    33.1  2718.3    54.1 2709.67
    69.9 2701.63    76.5 2697.31    85.2 2694.03    97.4 2685.78   115.5 2685.43
   118.8 2684.51   132.9 2675.07   141.6 2672.22   167.7 2660.73   182.9 2646.78
   198.2 2639.89  206.632631.427     215 2630.24  225.282631.431     257 2632.76
   283.5 2635.49   332.3 2635.19   353.9 2637.65   393.4 2646.86   408.1 2649.38
   423.7 2654.16   434.9 2655.19     452 2660.35     486 2668.65   521.6 2680.07
#Mann= 3 ,-1,0
       0      .1       0  206.63    .045       0  225.28      .1       0
Bank Sta=206.63,225.28
XS Rating Curve= 0 ,0
Exp/Cntr(USF)=0,0
Exp/Cntr=0.3,0.1

Type RM Length L Ch R = 1 ,15306   ,186.5,187.3,188.3
XS GIS Cut Line= 4
2188944.07911033604174.3298602352188937.85240717604406.932693466
2189070.25923084604495.9872149922189199.36329047604612.331100348
#Sta/Elev= 30
       0 2713.53    18.9 2704.67    26.9 2699.77    42.9 2696.92    86.9 2679.99
   102.9 2669.05   126.9 2667.77   142.8 2660.46   196.3 2647.24   214.9 2641.83
     225 2639.99   245.1 2638.98   264.4 2635.49   278.9 2633.99   298.2    2635
   317.4 2631.37   351.2 2630.51  353.592629.795   360.8 2628.18   370.5 2628.42
  374.582629.795   385.8  2635.2   414.3 2638.95   459.4 2652.37   471.7 2652.55
     481    2651   497.1 2652.54   519.1 2657.78   540.2 2660.33     566 2666.06
#Mann= 3 ,-1,0
       0      .1       0  353.59    .045       0  374.58      .1       0
Bank Sta=353.59,374.58
XS Rating Curve= 0 ,0
Exp/Cntr=0.3,0.1

Type RM Length L Ch R = 1 ,15119   ,218.9,204,189
XS GIS Cut Line= 4
2188693.67884464604586.9955888162188876.27286453604582.749723373
2188978.67881293604665.1458999492189145.17067645604690.749231653
#Sta/Elev= 30
       0 2698.46    29.4 2684.65    46.5 2675.07    50.5 2673.86    82.5 2659.49
     102 2652.18   114.5  2646.3   134.5 2639.75   154.5 2632.16   162.5 2630.94
   174.5 2630.56   192.8 2632.37   208.2 2630.74   235.5 2630.48  250.522628.654
   255.4 2627.15   261.1 2626.54   264.7  2626.7  271.362628.653   275.8 2630.37
     295  2632.3   310.9 2631.34   319.6  2632.5   335.8 2633.18   356.1 2635.96
   371.5 2640.33   400.6 2646.48   412.7 2648.12   425.8 2651.78   482.5  2661.9
#Mann= 3 ,-1,0
       0      .1       0  250.52    .045       0  271.36      .1       0
Bank Sta=250.52,271.36
XS Rating Curve= 0 ,0
Exp/Cntr(USF)=0,0
Exp/Cntr=0.3,0.1

Type RM Length L Ch R = 1 ,14915   ,285.5,293.3,296.3
XS GIS Cut Line= 4
2188753.65910721604897.619905843 2188871.7211861604828.518923171
2189002.28339833604713.1650846632189136.03868207604731.075843738
#Sta/Elev= 30
       0 2696.04    24.6 2686.34      40 2681.95    44.6 2679.47    57.7 2677.37
   100.2 2658.38     122 2641.75  143.722626.957     148 2625.93   156.5 2625.43
  165.23 2626.96   190.5 2628.01   202.3  2629.5   217.5  2628.8   228.1 2630.31
   238.8 2630.79   254.8 2631.07   262.7  2630.3   272.7 2631.39     284  2630.5
   298.2 2630.62   308.2 2633.63     317 2634.62   337.1 2639.77   365.4 2645.35
     391 2649.27   409.8 2653.62     434 2657.69   442.1 2660.37     446 2660.95
#Mann= 3 ,-1,0
       0      .1       0  143.72    .045       0  165.23      .1       0
Bank Sta=143.72,165.23
XS Rating Curve= 0 ,0
Exp/Cntr=0.3,0.1

Type RM Length L Ch R = 1 ,14621   ,215.8,223.3,227.3
XS GIS Cut Line= 4
 2188895.1384461605105.5057624012189038.67227535605037.230211189
2189147.16934409604993.149992992 2189233.0646519604878.743666104
#Sta/Elev= 30
       0 2690.63      10 2687.78    36.6 2678.84    47.3 2674.04    65.9 2663.83
     103 2648.82   125.2 2641.98   136.1 2639.92   156.2    2634   160.1 2632.33
   169.2 2626.62   173.5 2624.78   178.6 2624.16   201.6 2623.75  207.942623.155
   221.5 2621.93   233.5 2622.25  236.892623.157   251.2 2628.51   282.5 2635.23
   299.6 2637.49     306 2640.58     311 2642.03   325.3  2643.3     341  2643.1
   353.9 2647.02   376.1 2650.27   386.1 2652.26   399.6 2653.79   419.1 2659.07
#Mann= 3 ,-1,0
       0      .1       0  207.94    .045       0  236.89      .1       0
Bank Sta=207.94,236.89
XS Rating Curve= 0 ,0
Exp/Cntr(USF)=0,0
Exp/Cntr=0.3,0.1

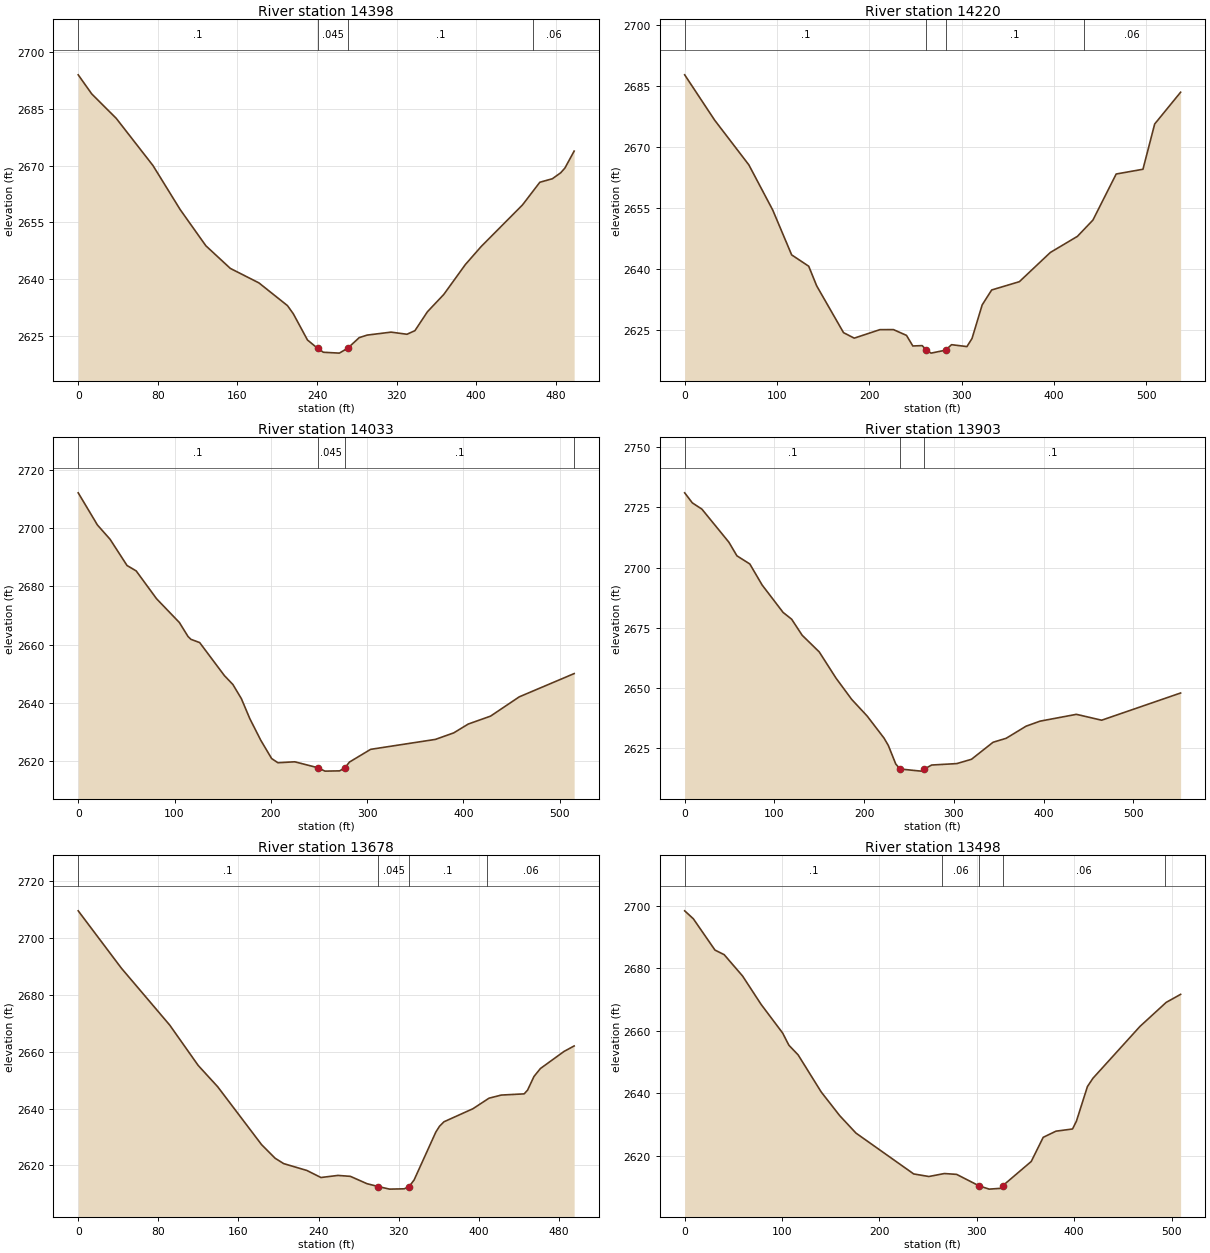
Type RM Length L Ch R = 1 ,14398   ,168.8,177.6,186.9
XS GIS Cut Line= 4
2188878.92149767605184.0210256372189089.89013626605231.119587776
2189220.96650449605231.8149744142189365.07939117605277.499405587
#Sta/Elev= 30
       0 2693.89    13.6 2688.86    38.2 2682.43    75.1 2670.01   102.5 2658.39
   128.3 2648.86   152.9  2642.9   181.6 2639.09   210.3  2633.1   216.2 2630.94
   230.4 2624.05  240.542621.865   246.4 2620.82   262.4 2620.59  270.732621.864
   282.4 2624.67   290.4 2625.34   314.4 2626.12   330.4 2625.56   338.4 2626.51
   350.9 2631.47   367.4 2636.05   389.1 2643.93     405 2648.68   446.5 2659.63
   463.9 2665.59   476.5 2666.52   484.9 2668.09   489.1 2669.33   498.4  2673.8
#Mann= 4 ,-1,0
       0      .1       0  240.54    .045       0  270.73      .1       0
  457.24     .06       0
Bank Sta=240.54,270.73
XS Rating Curve= 0 ,0
Exp/Cntr=0.3,0.1

Type RM Length L Ch R = 1 ,14220   ,184.6,187.1,189.8
XS GIS Cut Line= 4
2188864.12887086605237.0811838862189006.84852758605320.414137806
2189127.53763325605436.3139932582189322.80297839605497.769249212
#Sta/Elev= 30
       0  2687.8    32.5 2676.63    69.5 2665.64    95.4 2654.51   115.9 2643.47
   134.4 2640.67     143 2635.85   172.1 2624.32   183.7 2622.97   211.5 2625.06
   226.2 2625.07   240.3 2623.65   247.2 2621.04   257.3 2621.13  261.962620.012
   266.9 2619.28  282.742620.011   289.1 2621.36   305.8 2620.89   311.3 2622.88
   322.3 2631.15   332.6 2634.83   362.6 2636.87   396.2 2644.07   425.5 2648.03
   442.3 2652.04   467.5 2663.38   496.5 2664.55   509.2 2675.69   537.3 2683.52
#Mann= 4 ,-1,0
       0      .1       0  261.96    .045       0  282.74      .1       0
   432.6     .06       0
Bank Sta=261.96,282.74
XS Rating Curve= 0 ,0
Exp/Cntr(USF)=0,0
Exp/Cntr=0.3,0.1

Type RM Length L Ch R = 1 ,14033   ,149,129.9,120.1
XS GIS Cut Line= 4
2188706.08673913605344.1876229462188887.40814683605426.964787333
2188929.05446375605497.9736749382189125.34667348605623.966204744
#Sta/Elev= 30
       0 2712.15    19.9 2701.13    33.1 2696.19    50.7 2687.19    60.2 2685.33
    81.4 2675.75     105 2667.62     114 2662.82     117 2661.84   126.1 2660.72
   151.8 2649.37   160.6 2646.32   169.4 2641.46   178.2 2634.57   189.5  2627.2
   200.8  2620.9   207.3 2619.45   224.9 2619.77  248.612617.756   256.2 2616.57
   271.4 2616.66  277.082617.757   281.6 2619.68   303.6 2624.05   370.9 2627.47
   389.9 2629.71   404.9 2632.73   428.1 2635.46   457.9 2642.08   514.9 2650.07
#Mann= 4 ,-1,0
       0      .1       0  248.61    .045       0  277.08      .1       0
  514.89     .06       0
Bank Sta=248.61,277.08
XS Rating Curve= 0 ,0
Exp/Cntr(USF)=0,0
Exp/Cntr=0.3,0.1

Type RM Length L Ch R = 1 ,13903   ,212.8,225.5,232.6
XS GIS Cut Line= 4
2188598.45256339605439.2032346182188794.41121398 605558.51691092
2188882.11371604605554.9816520732189083.51727644605676.928357741
#Sta/Elev= 30
       0 2731.02     8.5 2726.86    19.2 2724.25    49.3  2710.5    58.2 2704.87
    72.6 2701.47    86.3 2692.75   109.7 2681.35   119.2 2678.54   130.9 2671.89
   149.9 2664.98   168.6  2654.1   186.1 2645.25   203.4 2638.31   222.1  2629.2
   226.9 2626.15   235.2 2618.43  239.922616.354   263.2 2615.47  267.072616.354
   275.2    2618   303.2  2618.6   319.6 2620.39   343.6 2627.45   358.2  2629.1
   380.4 2634.13     396 2636.22   436.5 2639.05   464.6 2636.61   552.6 2647.91
#Mann= 3 ,-1,0
       0      .1       0  239.92    .045       0  267.07      .1       0
Bank Sta=239.92,267.07
XS Rating Curve= 0 ,0
Exp/Cntr=0.3,0.1

Type RM Length L Ch R = 1 ,13678   ,175.9,180.2,183.2
XS GIS Cut Line= 4
2188548.02959614 605568.614703342188715.11858726605706.491238975
2188814.56364322605776.4052130552188937.29453306605874.169761181
#Sta/Elev= 30
       0 2709.42    43.1 2689.28    91.4 2669.28   119.8 2655.12   139.2 2647.67
   183.1  2627.3   196.6 2622.54   205.1 2620.66   228.3 2618.25   242.3 2615.78
   259.3 2616.51   271.7 2616.19   288.2 2613.62   299.5 2612.61   310.8  2611.7
   325.5 2611.81  330.352612.609   335.3  2614.9     357 2631.73   360.7 2633.78
   365.1 2635.34     394 2639.92   410.1 2643.63   422.4 2644.73   445.2 2645.15
   448.6 2646.46     455 2651.26   461.4 2654.04   485.1 2660.07   495.1 2661.97
#Mann= 4 ,-1,0
       0      .1       0   299.5    .045       0  330.35      .1       0
  408.19     .06       0
Bank Sta=299.5,330.35
XS Rating Curve= 0 ,0
Exp/Cntr(USF)=0,0
Exp/Cntr=0.3,0.1

Type RM Length L Ch R = 1 ,13498   ,155.5,165.3,171.4
XS GIS Cut Line= 4
 2188491.3917659 605630.991836132188617.44940952605828.438516673
2188688.02645527605911.7365492342188805.77000811606028.533872467
#Sta/Elev= 30
       0  2698.3     8.9 2695.76    31.1 2685.77    40.6 2684.29    59.5 2677.46
    78.5 2668.41   100.6 2659.27     107 2655.38   116.5 2652.29   140.2 2640.45
   159.2 2632.88   175.9 2627.31   235.2 2614.26   250.8 2613.44   266.7 2614.39
   279.3 2614.12   302.42610.446   312.7 2609.41   324.4 2609.66  326.472610.448
   355.9 2618.24   368.2 2625.96   381.3 2627.92   398.3 2628.62   402.3 2631.12
   413.6 2642.17   419.3 2644.83   467.6 2661.39   494.5 2669.06   509.3 2671.62
#Mann= 5 ,-1,0
       0      .1       0  264.26     .06       0   302.4    .045       0
  326.47     .06       0  493.43      .1       0
Bank Sta=302.4,326.47
XS Rating Curve= 0 ,0
Exp/Cntr=0.3,0.1