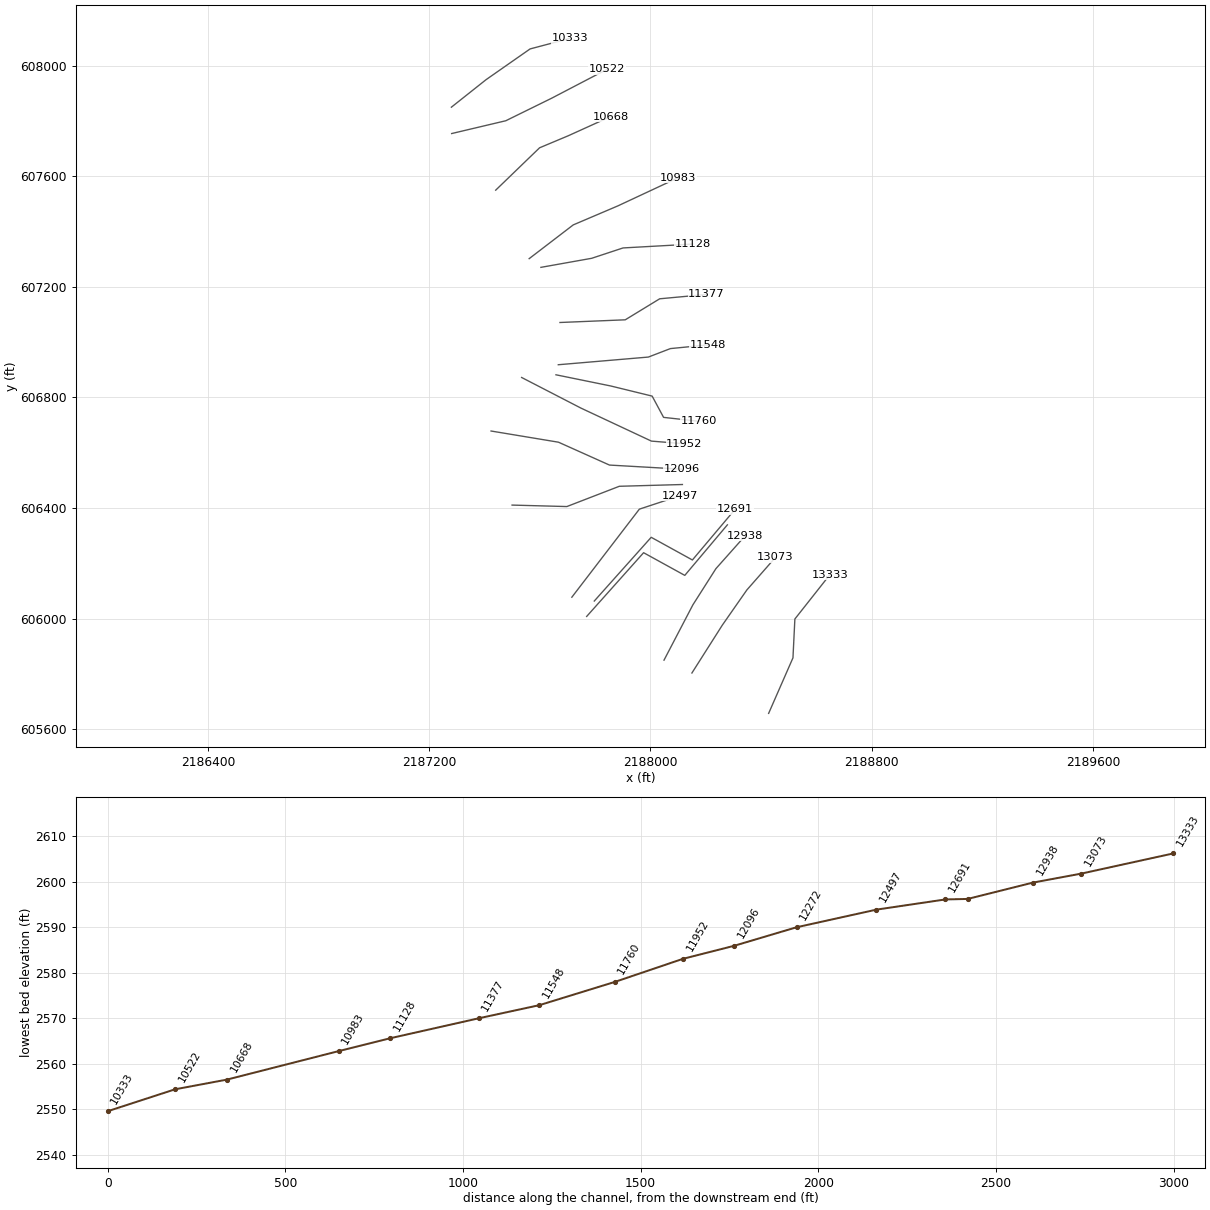
HEC-RAS study MARSHFK.prj: MARSHFK

--- MARSHFK.g01 (geometry) --- (continued)

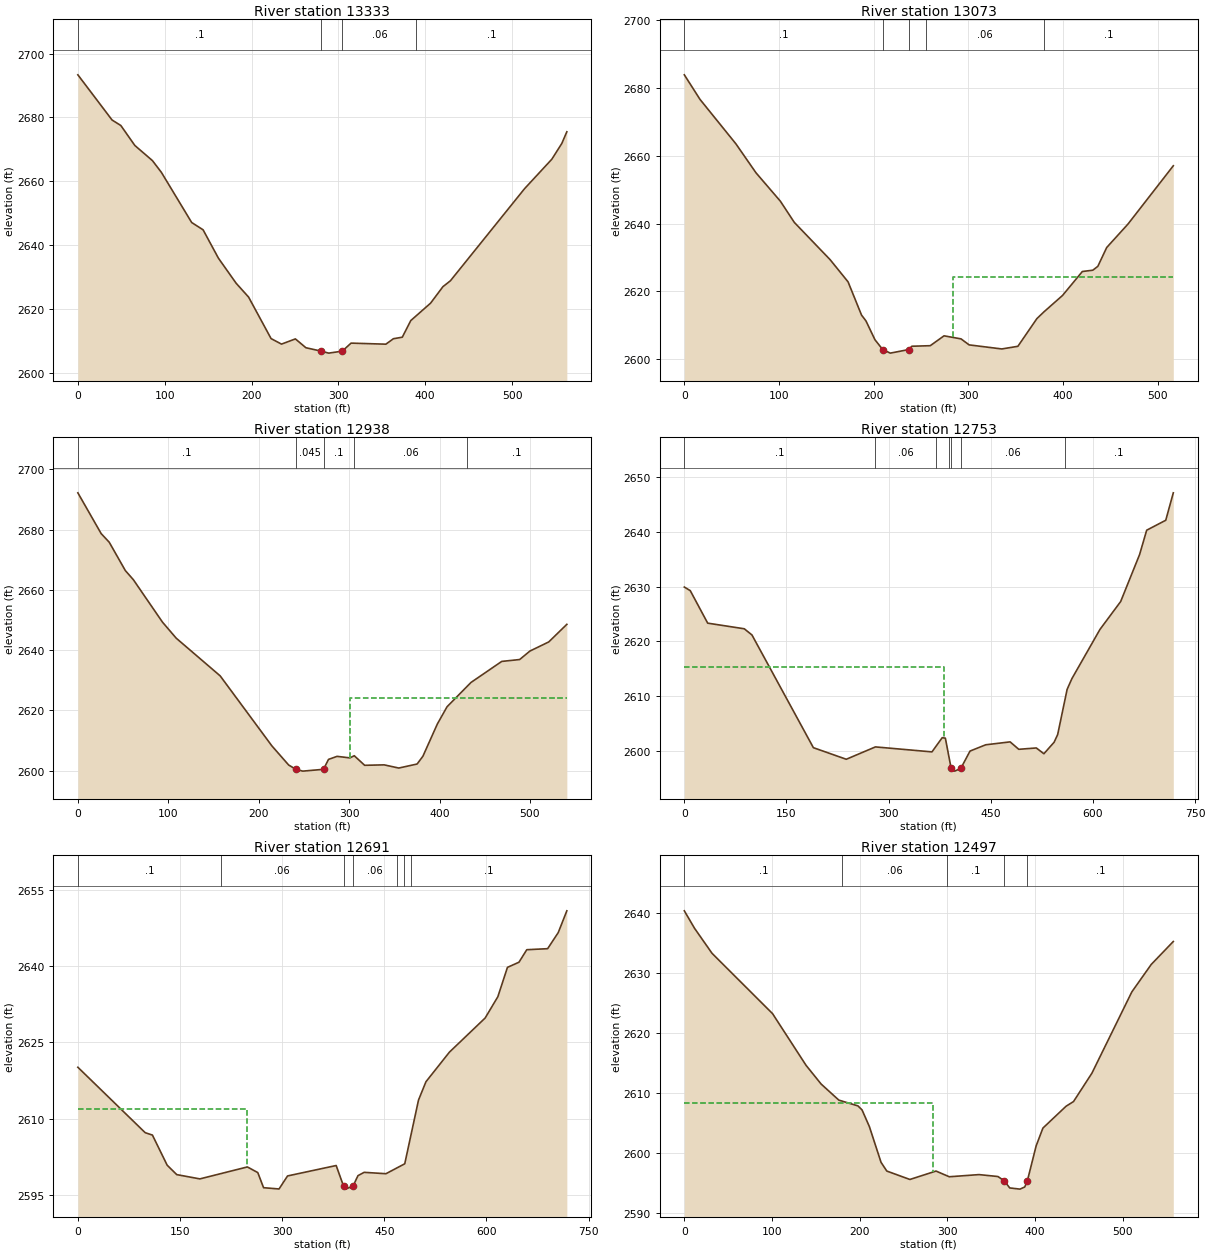
Type RM Length L Ch R = 1 ,13333   ,264.7,259.3,250
XS GIS Cut Line= 4
2188427.10694871 605657.081734512188515.03758285605857.942888959
2188521.93410317605998.459490569 2188647.7955991606157.941523072
#Sta/Elev= 30
       0 2693.35    39.4 2679.21    49.5 2677.49    65.6 2671.25    85.9  2666.5
    96.2 2662.83   131.1 2647.13   144.2 2644.86   161.8 2636.01   182.2 2628.16
   196.6 2623.81   222.5 2610.82   234.5 2609.09   250.5 2610.72   262.6 2607.96
  280.072606.895   288.9 2606.27  304.522606.895   314.6  2609.4   354.7 2609.07
   363.4 2610.78   373.6 2611.25   383.4 2616.46   406.2 2621.91   420.4 2627.06
     429  2628.9   514.4 2657.72   545.8 2666.94   557.3 2671.87   563.1 2675.53
#Mann= 4 ,-1,0
       0      .1       0  280.07    .045       0  304.52     .06       0
  389.95      .1       0
Bank Sta=280.07,304.52
XS Rating Curve= 0 ,0
Exp/Cntr(USF)=0,0
Exp/Cntr=0.3,0.1

Type RM Length L Ch R = 1 ,13073   ,133.2,135.6,134.7
XS GIS Cut Line= 4
2188149.79577551 605803.149820372188259.88158825605976.581306193
2188348.39020149606103.5600784682188451.59884538606221.125650177
#Sta/Elev= 30
       0 2683.84    16.6 2676.59    54.5  2663.5    75.6 2655.01   101.5 2646.59
   116.2 2640.35     154 2629.38     173 2622.83   187.2 2613.05   191.9 2611.32
   201.4 2605.77  209.572602.892   217.6 2601.83  237.312602.895   240.3 2603.86
   259.8 2604.02   274.4 2606.93   292.3 2606.03   300.9 2604.26   335.4 2603.06
   352.4 2603.84   372.5 2612.01   380.2 2614.06   399.6 2618.83   420.5 2625.88
   431.6 2626.27   436.9 2627.42   446.2 2632.94   468.8 2639.89   516.6 2657.04
#Mann= 5 ,-1,0
       0      .1       0  209.57    .045       0  237.31      .1       0
  255.42     .06       0   380.2      .1       0
#XS Ineff= 2 , 0
                          284.19         2624.31
Permanent Ineff=
       F       F
Bank Sta=209.57,237.31
XS Rating Curve= 0 ,0
Exp/Cntr(USF)=0,0
Exp/Cntr=0.3,0.1

Type RM Length L Ch R = 1 ,12938   ,198.6,184.2,174.8
XS GIS Cut Line= 4
 2188048.8991957605849.6065165792188153.26320243606049.632533207
 2188236.5856654606180.6934096412188342.82464229606300.111893421
#Sta/Elev= 30
       0 2692.19    25.8 2678.65    34.7  2675.8    52.5  2666.4    61.4 2663.36
    93.6 2649.28   108.8 2643.96   157.4 2631.46   214.6 2608.23   233.2 2601.87
  241.262600.458   248.8 2599.86  271.692600.458   277.2 2603.75   286.7 2604.76
   300.9 2604.25   305.7 2604.97   317.2 2601.79   338.8 2601.94   354.9 2600.88
   375.2 2602.22   381.6 2604.79   397.6  2615.5   408.3 2621.21   434.8 2629.28
   468.8 2636.26   488.6 2636.88     500  2639.7   520.8 2642.72   540.8 2648.56
#Mann= 5 ,-1,0
       0      .1       0  241.26    .045       0  271.69      .1       0
  305.62     .06       0  430.92      .1       0
#XS Ineff= 2 , 0
                          301.08         2624.28
Permanent Ineff=
       F       F
Bank Sta=241.26,271.69
XS Rating Curve= 0 ,0
Exp/Cntr=0.3,0.1

Type RM Length L Ch R = 1 ,12753   ,62.3,62.7,62.4
XS GIS Cut Line= 4
2187769.36257417606007.7691965772187975.12437771606238.286223987
2188124.03074068606156.2516464432188277.95782191606339.072722959
#Sta/Elev= 30
       0 2629.93     8.7 2629.28    34.3 2623.33      88  2622.3    99.3 2621.17
   189.5 2600.55   237.8 2598.43   280.6 2600.69   363.6 2599.78   378.7 2602.38
   383.3 2602.29  391.812596.759     397 2596.26     4062596.765   419.5 2599.93
   442.6 2601.08   478.4 2601.61   491.1 2600.25   516.8  2600.5     528 2599.44
     543 2601.55   548.2 2602.95   562.1 2611.22   569.1 2613.18   610.3 2622.18
   640.7 2627.28   668.5 2635.88   678.9 2640.33   706.9 2642.15     718 2647.17
#Mann= 7 ,-1,0
       0      .1       0     280     .06       0  368.99      .1       0
  388.99     .06       0  391.81    .045       0     406     .06       0
     559      .1       0
#XS Ineff= 2 , 0
          381.23 2615.24
Permanent Ineff=
       F       F
Bank Sta=391.81,406
XS Rating Curve= 0 ,0
Exp/Cntr(USF)=0,0
Exp/Cntr=0.3,0.1

Type RM Length L Ch R = 1 ,12691   ,186.7,194.2,205.8
XS GIS Cut Line= 4
  2187796.845052606063.4702900332188002.60685554606293.987317443
2188151.51321851606211.9527398992188305.44029974606394.773816415
#Sta/Elev= 30
       0  2620.1    98.8 2607.25   109.5 2606.77   131.1 2600.86   145.2    2599
   179.2 2598.16   248.9 2600.51   264.2  2599.4   272.7 2596.43   295.4 2596.18
   307.9 2598.74   379.3 2600.79   390.2 2596.72     393 2596.15   404.12596.756
   411.3  2598.8   420.4 2599.45   452.4 2599.18     480 2601.13   500.2 2613.65
   511.1 2617.25   545.6 2623.07     598 2629.77   616.7 2633.96   630.8 2639.73
   647.7 2640.74   659.2  2643.2   689.8  2643.4   705.4 2646.57     718 2650.84
#Mann= 7 ,-1,0
       0      .1       0     210     .06       0   390.2    .045       0
   404.1     .06       0  468.99      .1       0  478.99     .06       0
     489      .1       0
#XS Ineff= 2 , 0
          248.95 2611.97
Permanent Ineff=
       F       F
Bank Sta=390.2,404.1
XS Rating Curve= 0 ,0
Exp/Cntr(USF)=0,0
Exp/Cntr=0.3,0.1

Type RM Length L Ch R = 1 ,12497   ,237.8,224.9,219.9
XS GIS Cut Line= 3
2187715.77761443606077.3350407832187959.78110656606395.822929244
2188108.25677538 606444.85478359
#Sta/Elev= 30
       0 2640.28    11.6 2637.38    31.6  2633.2   100.6 2623.15   138.8 2614.54
     156 2611.42   176.2 2608.74     198 2607.78   202.7  2607.1   211.1  2604.3
   224.3 2598.38   230.9 2596.92   257.2 2595.52     287 2596.92   302.1 2595.97
   336.1 2596.33   357.6 2596.01  364.77 2595.29   371.1 2594.11   382.8 2593.91
   388.2 2594.27  391.16 2595.29   401.2 2601.12   408.9 2604.08   435.3 2607.72
   443.8  2608.5   464.8 2613.23   510.3 2626.77   532.4 2631.34   557.6 2635.17
#Mann= 5 ,-1,0
       0      .1       0     180     .06       0     300      .1       0
  364.77    .045       0  391.16      .1       0
#XS Ineff= 2 , 0
          283.75 2608.21
Permanent Ineff=
       F       F
Bank Sta=364.77,391.16
XS Rating Curve= 0 ,0
Exp/Cntr(USF)=0,0
Exp/Cntr=0.3,0.1

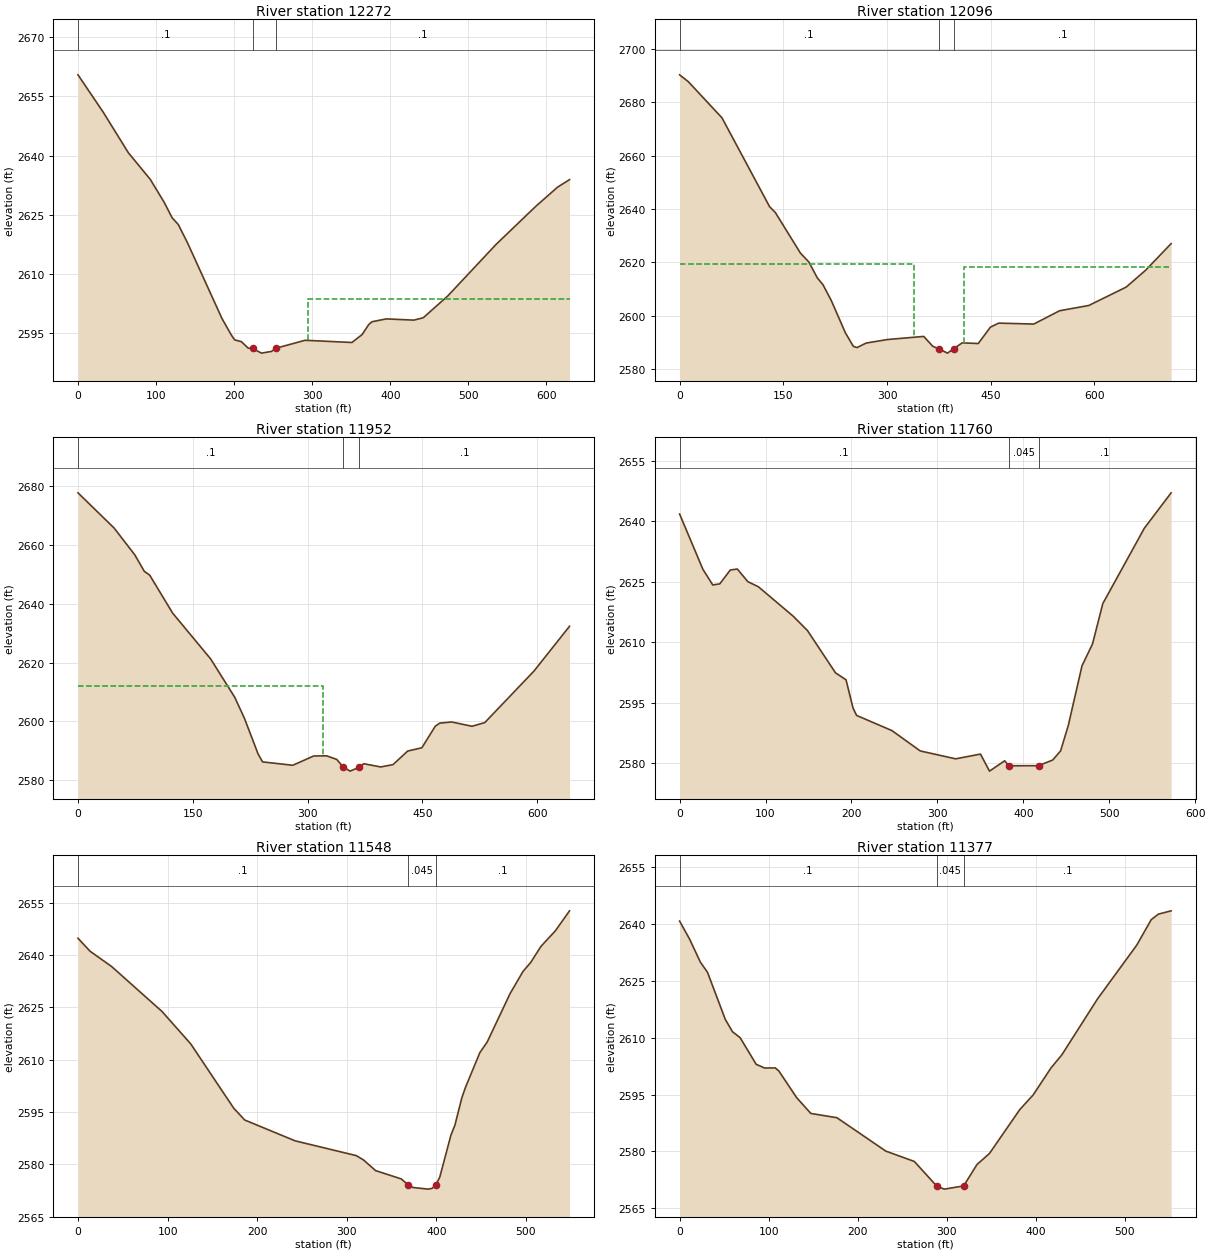
Type RM Length L Ch R = 1 ,12272   ,189,175.4,166
XS GIS Cut Line= 4
2187499.70819662 606410.54133069 2187697.6638726606405.219941551
2187887.35219464 606478.549477662188115.39509383606484.970201029
#Sta/Elev= 30
       0 2660.44    32.5 2650.93    64.5 2640.73    92.5 2634.01   110.1 2628.29
   120.5  2624.3   128.5 2622.55   140.5 2617.84   184.5 2598.75   196.5 2594.58
   200.7 2593.38   209.3 2592.93   217.9  2591.3   223.5 2591.21     235 2590.03
   247.9 2590.47   253.4 2591.26   290.8 2593.28   350.8 2592.72   363.9 2594.73
   372.3 2597.26   376.5 2597.97   394.8 2598.69   430.2 2598.38   442.2 2598.98
   473.7 2604.52   535.4 2617.53   586.3 2627.17   614.3 2632.04   629.5 2633.92
#Mann= 3 ,-1,0
       0      .1       0   223.5    .045       0   253.4      .1       0
#XS Ineff= 2 , 0
                          294.35         2603.77
Permanent Ineff=
       F       F
Bank Sta=223.5,253.4
XS Rating Curve= 0 ,0
Exp/Cntr(USF)=0,0
Exp/Cntr=0.3,0.1

Type RM Length L Ch R = 1 ,12096   ,144.1,144,143.8
XS GIS Cut Line= 4
2187423.70871402606678.473648096 2187667.4283366606638.031090637
2187851.73120118606555.3210585292188113.10771441606540.421168939
#Sta/Elev= 30
       0 2690.23    12.6 2687.67    61.3 2674.11   130.2 2640.81   138.3 2638.71
   174.8 2623.42     187 2620.11   199.2 2614.14   207.3 2611.62   219.4 2605.66
   239.7 2593.61   251.3  2588.5   256.6 2588.04   269.8 2589.73   300.5 2591.05
   353.1 2592.22   366.2 2588.51  374.652587.607   387.5 2585.96  396.282587.606
   408.7  2589.8     432 2589.56   449.5 2595.69   461.5  2597.2   512.2 2596.85
   549.7 2601.85   591.8 2603.81   645.8 2610.69   673.9 2616.99   710.9 2626.99
#Mann= 3 ,-1,0
       0      .1       0  374.65    .045       0  396.28      .1       0
#XS Ineff= 2 , 0
          339.64 2619.31  410.72         2618.11
Permanent Ineff=
       F       F
Bank Sta=374.65,396.28
XS Rating Curve= 0 ,0
Exp/Cntr(USF)=0,0
Exp/Cntr=0.3,0.1

Type RM Length L Ch R = 1 ,11952   ,199.6,192.3,189.3
XS GIS Cut Line= 4
2187534.25185519606872.135688626 2187748.5449431606761.424250225
2188003.47588664606641.9607314132188122.44399028606632.328292683
#Sta/Elev= 30
       0 2677.72    47.2 2665.75    74.2 2656.64    86.7 2651.01    93.6 2649.76
   123.7 2636.81   173.3 2621.25   204.8  2608.2   217.4 2601.08   235.2 2588.99
   241.1 2586.24   280.6 2585.09   307.8 2588.24   324.7  2588.3     338 2587.08
  346.262584.551   355.4  2583.1  367.742584.475   373.3 2585.62   395.4 2584.52
   411.5 2585.31   430.7 2589.93   449.2 2591.04   466.7 2598.36   472.7 2599.43
   488.2 2599.81   514.7 2598.35   531.4  2599.6   595.7 2617.13   642.1 2632.35
#Mann= 3 ,-1,0
       0      .1       0  346.26    .045       0  367.74      .1       0
#XS Ineff= 2 , 0
          320.43 2612.07
Permanent Ineff=
       F       F
Bank Sta=346.26,367.74
XS Rating Curve= 0 ,0
Exp/Cntr=0.3,0.1

Type RM Length L Ch R = 1 ,11760   ,191,212,239.3
XS GIS Cut Line= 5
2187658.35579499606881.8554411942187856.31147097606841.412883735
2188006.05072004606804.7417703652188047.33958377606727.820051622
 2188175.1653811606713.680029794
#Sta/Elev= 30
       0 2641.81    27.1  2628.1    38.6 2624.21    46.8 2624.48      59 2627.92
    67.2 2628.16    79.4 2625.03    91.7 2623.76   132.5  2616.4   148.8  2612.9
   181.5 2602.39   193.7 2600.68   201.9 2593.64     206 2591.84   247.2 2588.06
   280.1 2583.02   321.3 2581.06   350.2 2582.24   360.7 2578.01   378.4 2580.58
     383 2579.34  417.742579.357   434.3 2580.77   443.5 2583.05   452.4 2589.34
   468.4 2604.17   480.6 2609.57   492.6 2619.59   540.9 2638.28   572.1 2647.07
#Mann= 3 ,-1,0
       0      .1       0     383    .045       0  417.74      .1       0
Bank Sta=383,417.74
XS Rating Curve= 0 ,0
Exp/Cntr(USF)=0,0
Exp/Cntr=0.3,0.1

Type RM Length L Ch R = 1 ,11548   ,166.7,170.7,172.3
XS GIS Cut Line= 4
2187666.72847561606918.2290823172187992.39749093606946.006733624
2188072.06614496606976.6571412962188207.84138885606990.024043368
#Sta/Elev= 30
       0 2644.85    13.5 2641.12    37.4 2636.77    93.8 2623.85   125.9 2614.54
   173.9 2596.09   186.1 2592.73   242.3 2586.76   310.6 2582.52   318.5 2581.31
   332.2 2578.22   360.9 2575.83  368.432574.116   373.8 2573.38   390.9 2572.91
   395.2 2573.13  399.482574.115   403.8 2576.38   416.3 2588.43   420.7 2591.26
   428.4 2599.08   432.4 2602.04   448.5 2612.03   456.7 2615.08   482.3    2629
   496.7 2635.33   505.4 2637.95   516.8 2642.54   532.9 2647.01   548.6 2652.71
#Mann= 3 ,-1,0
       0      .1       0  368.43    .045       0  399.48      .1       0
Bank Sta=368.43,399.48
XS Rating Curve= 0 ,0
Exp/Cntr(USF)=0,0
Exp/Cntr=0.3,0.1

Type RM Length L Ch R = 1 ,11377   ,250,249.5,245.8
XS GIS Cut Line= 4
2187672.89448882607071.0463157252187908.79903415607080.753960978
2188033.24415654607156.7635882672188202.37685367607172.518536603
#Sta/Elev= 30
       0  2640.8    11.3 2636.02    23.3 2629.98    31.3  2627.3    51.3 2614.85
    59.3 2611.61      68    2610      86 2602.98    95.4 2602.01   107.4 2602.03
   111.4 2601.23   131.4 2594.19   147.3 2590.01   176.6 2588.88   231.5 2580.06
   263.5 2577.33   288.52570.862   297.1 2570.02  318.86 2570.86   333.8  2576.5
   347.9 2579.45   381.9 2591.03   396.9 2594.89     417 2602.05   429.1 2605.48
   469.2 2620.27   513.2 2634.46   529.5  2641.2   537.5 2642.65   551.8 2643.52
#Mann= 3 ,-1,0
       0      .1       0   288.5    .045       0  318.86      .1       0
Bank Sta=288.5,318.86
XS Rating Curve= 0 ,0
Exp/Cntr=0.3,0.1

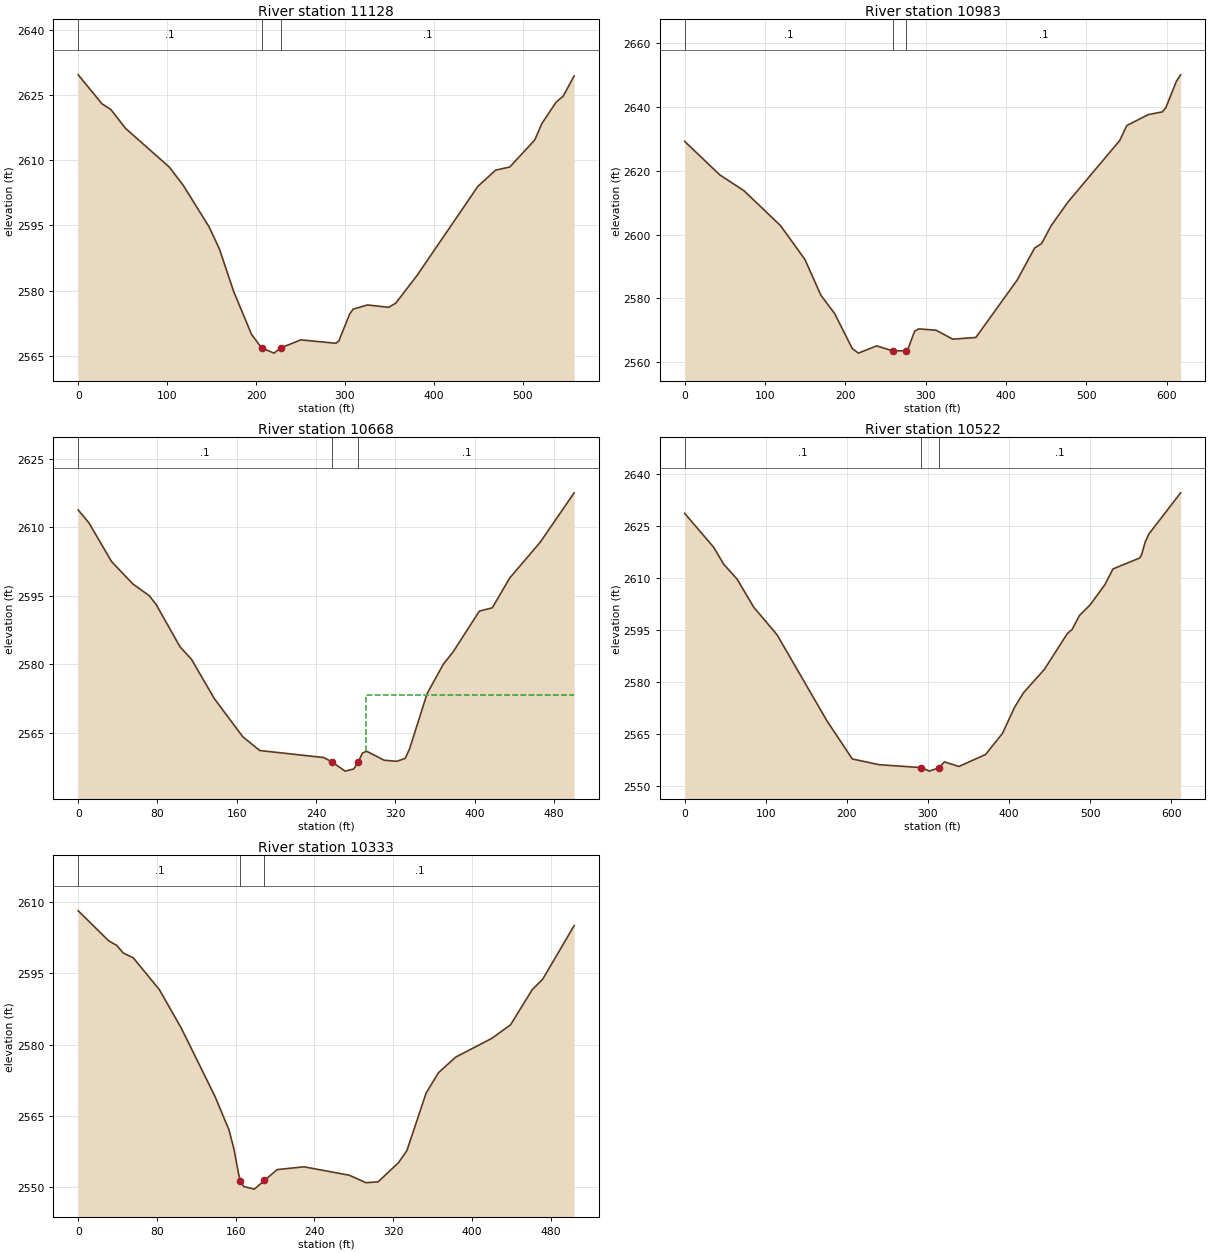
Type RM Length L Ch R = 1 ,11128   ,143.4,145.1,143.9
XS GIS Cut Line= 4
2187603.87138214607270.5140729792187787.49123578607303.272544521
2187900.92409863607340.7525031862188152.49529807607354.717956844
#Sta/Elev= 30
       0 2629.59    26.7 2622.94    36.9 2621.58    53.1 2617.32   102.6 2608.36
   118.1 2604.22   147.4 2594.59   158.8 2589.59     175 2579.74   194.9 2569.97
   206.22566.848   220.2 2565.63  228.112566.847   250.4 2568.68   289.9 2567.89
   293.1 2568.39   305.2 2574.53   309.2 2575.73   325.3  2576.7   349.3 2576.16
   357.3 2577.13   381.4 2583.55   449.5 2603.93   469.5 2607.68   485.5 2608.41
   513.6 2614.62   521.6  2618.4   537.6 2623.31   545.6 2624.69   557.9 2629.34
#Mann= 3 ,-1,0
       0      .1       0   206.2    .045       0  228.11      .1       0
Bank Sta=206.2,228.11
XS Rating Curve= 0 ,0
Exp/Cntr(USF)=0,0
Exp/Cntr=0.3,0.1

Type RM Length L Ch R = 1 ,10983   ,314.4,314.3,313.8
XS GIS Cut Line= 4
 2187561.5141443607301.9971366452187720.80001858607424.069560326
2187882.27896737607492.9077533412188100.88328344607595.088576593
#Sta/Elev= 30
       0 2629.23    43.7 2618.73    73.9 2613.74   119.3 2602.81   149.7 2592.19
   169.6 2580.97   186.8 2575.19   208.7 2564.23   216.3  2562.8   239.1 2565.08
     259  2563.5  275.532563.535   278.3 2564.29   286.4  2569.7   291.3 2570.41
   313.1 2569.98   333.8 2567.18   362.6 2567.72     414 2585.73   435.7 2595.77
   444.5 2597.21   456.1 2602.71   477.1 2610.16   541.7 2629.51   550.5 2634.19
     577 2637.62   594.7 2638.48   599.1 2639.82   612.3 2648.12   617.5 2650.11
#Mann= 3 ,-1,0
       0      .1       0     259    .045       0  275.53      .1       0
Bank Sta=259,275.53
XS Rating Curve= 0 ,0
Exp/Cntr=0.3,0.1

Type RM Length L Ch R = 1 ,10668   ,144.5,145.8,146.5
XS GIS Cut Line= 4
2187440.53005677607549.7411117572187599.10745312 607702.99711897
2187702.61957996607746.4477248872187855.33328983607815.667573525
#Sta/Elev= 30
       0 2613.81    10.7 2611.02    33.7 2602.49    55.1  2597.6    71.8 2594.99
    78.6 2593.11   102.8 2583.78   114.3 2581.07   137.3 2572.47   166.1 2564.07
   183.2 2561.06   247.7 2559.52  255.882558.593   269.4 2556.54   278.1 2557.01
  282.742558.594   286.8 2560.51   291.1  2560.9   308.8 2558.93   321.5 2558.69
     330 2559.34   334.5 2561.48   352.1 2573.54   368.5    2580   378.4  2582.7
   404.8 2591.62   417.9 2592.36   435.5  2598.9   466.3 2606.75   500.5 2617.57
#Mann= 3 ,-1,0
       0      .1       0  255.88    .045       0  282.74      .1       0
#XS Ineff= 2 , 0
                          290.69         2573.17
Permanent Ineff=
       F       F
Bank Sta=255.88,282.74
XS Rating Curve= 0 ,0
Exp/Cntr(USF)=0,0
Exp/Cntr=0.3,0.1

Type RM Length L Ch R = 1 ,10522   ,187.3,189.8,189.8
XS GIS Cut Line= 4
 2187281.3476929607754.5348051662187477.07975021 607800.85695071
2187642.84504486607882.3822417462187842.93674732607986.906693484
#Sta/Elev= 30
       0 2628.67    35.8  2618.9    48.1 2614.02    64.6 2609.75    85.1 2601.66
   113.9  2593.7   175.5 2568.88   206.7 2557.92   239.5 2556.27  291.872555.427
   301.6 2554.41  314.062555.428   320.2 2557.08   338.2 2555.75     371 2559.19
   391.9 2565.28   406.7 2572.75   417.8 2576.97   443.7 2583.76   471.9 2594.04
   477.9 2595.25   486.7 2599.21   500.2 2602.37   518.2 2608.13   528.2 2612.66
   560.9 2615.79   563.4 2616.69   567.9 2620.41   572.4 2622.71   611.6 2634.59
#Mann= 3 ,-1,0
       0      .1       0  291.87    .045       0  314.06      .1       0
Bank Sta=291.87,314.06
XS Rating Curve= 0 ,0
Exp/Cntr=0.3,0.1

Type RM Length L Ch R = 1 ,10333   ,168.8,169.5,170.4
XS GIS Cut Line= 4
2187280.34864677607849.9096221462187405.82700267607949.526026834
2187564.83011016608060.6366320632187709.46546696608098.950633866
#Sta/Elev= 30
       0 2608.13      31 2601.82    39.2 2600.85    45.7 2599.27      56 2598.23
    82.5 2591.54   104.7 2583.46   138.9 2569.11   153.1 2562.08   158.1 2558.13
   163.1 2552.63  164.842551.381     168 2550.15   178.9 2549.59  189.162551.412
   202.1  2553.7   229.4 2554.28   275.3 2552.52   292.3 2550.94   304.6 2551.12
   325.4 2555.16   333.9  2557.7   353.4 2569.79   365.9 2574.06   383.5 2577.36
   420.1  2581.3   439.2 2584.15   461.1 2591.51   471.9 2593.77   503.8 2605.02
#Mann= 3 ,-1,0
       0      .1       0  164.84    .045       0  189.16      .1       0
Bank Sta=164.84,189.16
XS Rating Curve= 0 ,0
Exp/Cntr(USF)=0,0
Exp/Cntr=0.3,0.1