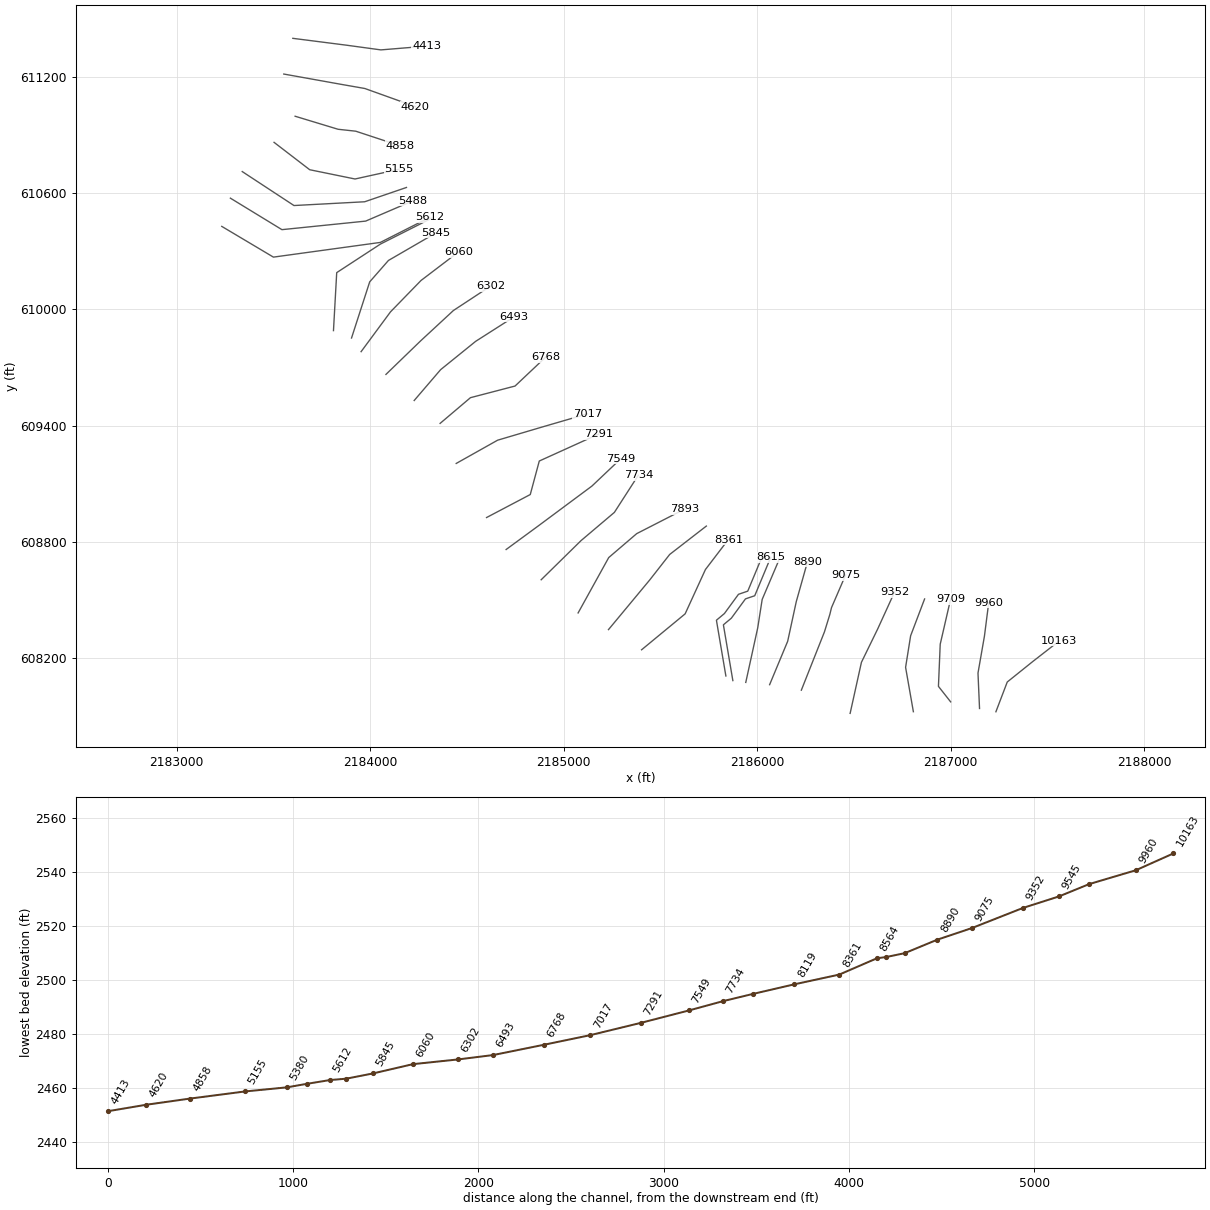
HEC-RAS study MARSHFK.prj: MARSHFK

--- MARSHFK.g01 (geometry) --- (continued)

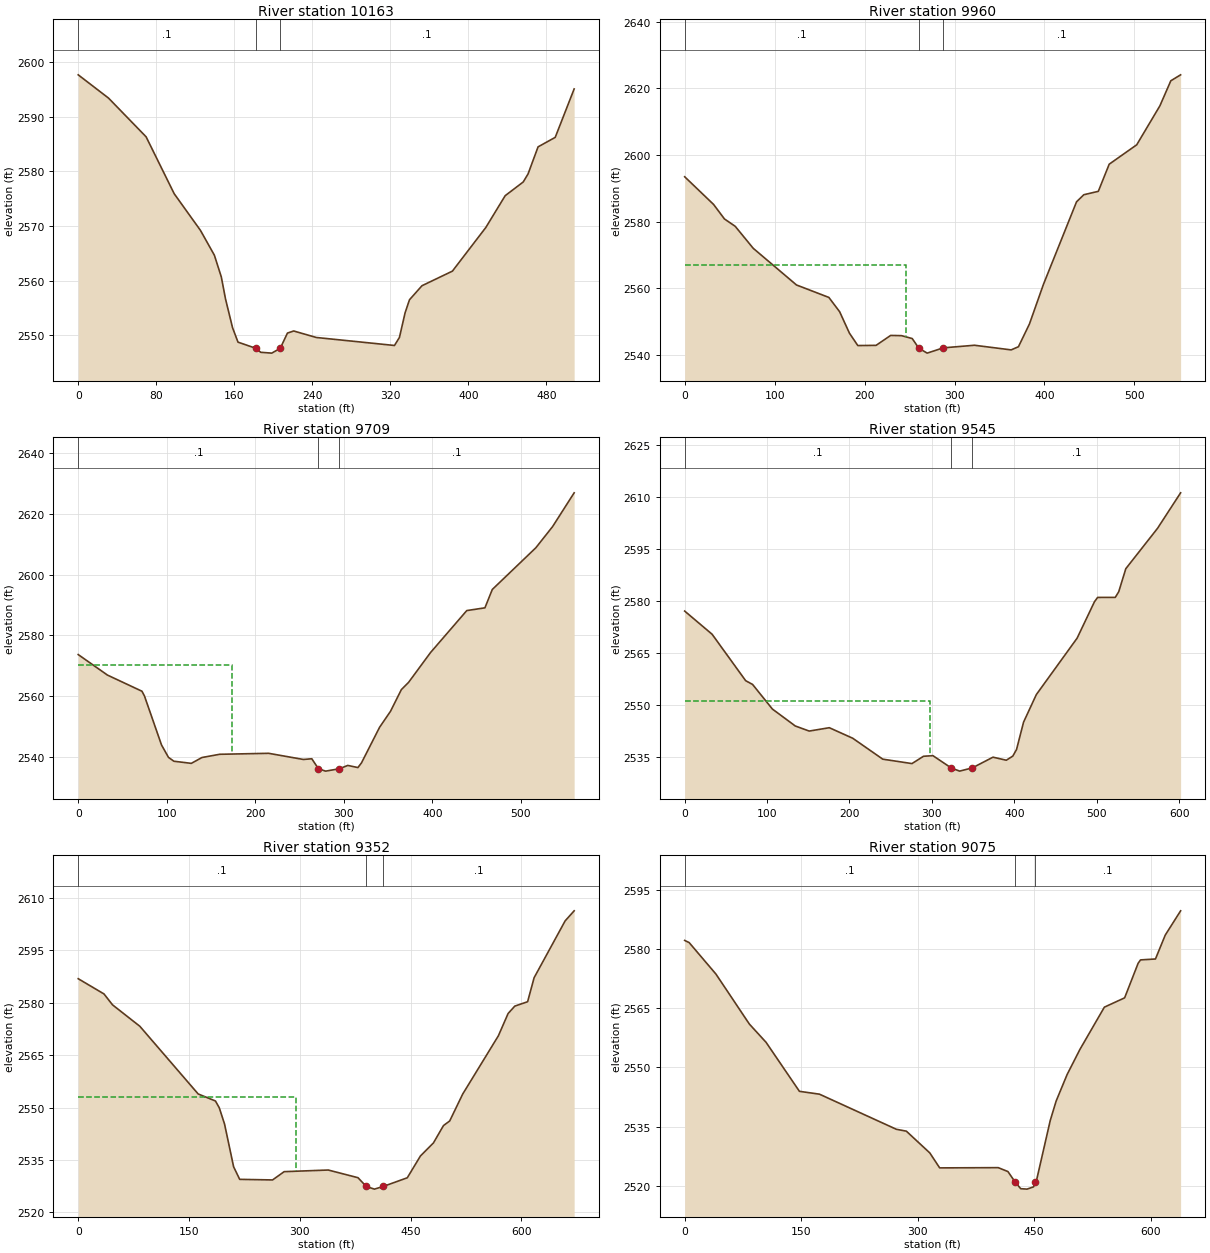
Type RM Length L Ch R = 1 ,10163   ,195.8,203.3,214.8
XS GIS Cut Line= 4
2187233.14556327607920.1023382792187291.74128427608073.933843872
2187425.23733826608181.1388930192187561.38737875608287.168557062
#Sta/Elev= 30
       0 2597.67    31.1 2593.41    69.6 2586.33    98.4 2575.92   125.3 2569.22
   139.6 2564.67   146.7  2560.7     151 2556.67   158.2 2551.42   163.8 2548.77
  182.11 2547.64   187.1 2546.91   198.4 2546.76  207.122547.638   214.5 2550.43
   220.9 2550.81   244.1 2549.62   324.2 2548.16   329.3 2549.63   335.1 2554.14
   339.6 2556.52   352.4 2559.09   383.6 2561.76   417.8 2569.73   437.7 2575.56
   456.2 2578.07   461.2 2579.56   471.4 2584.49     489 2586.23   508.4 2595.09
#Mann= 3 ,-1,0
       0      .1       0  182.11    .045       0  207.12      .1       0
Bank Sta=182.11,207.12
XS Rating Curve= 0 ,0
Exp/Cntr(USF)=0,0
Exp/Cntr=0.3,0.1

Type RM Length L Ch R = 1 ,9960    ,249.3,251.3,250.4
XS GIS Cut Line= 4
2187148.51739816607937.0217854912187140.54318346608120.073128196
2187173.81782746608310.8410431632187195.96167122608483.956829084
#Sta/Elev= 30
       0 2593.44    32.2 2585.12    44.2 2580.79    56.2 2578.57    76.2 2571.98
   124.3 2560.98   160.3 2557.24   172.3 2552.95   183.2 2546.51   192.5  2542.8
   212.8 2542.86     229 2545.84   241.2 2545.77     253  2544.9  260.322542.016
   269.6 2540.53 287.5282542.113   322.2 2542.89     363  2541.5   371.1 2542.45
   383.3 2549.26   398.9 2561.17   435.7 2585.93   443.8 2588.05   459.9 2589.07
     472 2597.21   502.6 2603.03   528.4 2614.74   540.5 2622.23   551.4 2624.02
#Mann= 3 ,-1,0
       0      .1       0  260.32    .045       0 287.528      .1       0
#XS Ineff= 2 , 0
          245.63 2567.07
Permanent Ineff=
       F       F
Bank Sta=260.32,287.528
XS Rating Curve= 0 ,0
Exp/Cntr=0.3,0.1

Type RM Length L Ch R = 1 ,9709    ,164.2,163.5,161.3
XS GIS Cut Line= 4
 2186999.3003515607971.2221395242186936.23203577608051.371457425
2186945.42949848608269.482715975 2186999.3003515608503.361053457
#Sta/Elev= 30
       0 2573.71      33 2566.98      72 2561.67    74.8 2560.15    94.1 2544.04
     102 2539.94   108.1 2538.68   127.8 2537.98   139.8  2539.9   159.8 2540.96
   215.1 2541.28   254.4 2539.26   263.9 2539.49  271.432536.201   279.5 2535.43
  294.932536.202   304.6  2537.3     316  2536.6     320 2538.12   340.5 2549.84
   352.8 2555.07   365.1  2562.2   373.3  2564.6     398 2574.36     439 2588.16
   459.5 2589.06   467.8 2595.08     517 2608.78   535.9 2615.72   560.3 2626.83
#Mann= 3 ,-1,0
       0      .1       0  271.43    .045       0  294.93      .1       0
#XS Ineff= 2 , 0
          173.72 2570.28
Permanent Ineff=
       F       F
Bank Sta=271.43,294.93
XS Rating Curve= 0 ,0
Exp/Cntr(USF)=0,0
Exp/Cntr=0.3,0.1

Type RM Length L Ch R = 1 ,9545    ,196,193.4,189
XS GIS Cut Line= 4
2186806.71985576607920.3357339072186766.51380449608149.746732359
2186792.52948473608312.9359992982186864.66387084608503.323477394
#Sta/Elev= 30
       0 2577.09    33.3 2570.39      74 2556.98    82.4  2555.9   106.4  2548.8
   134.2  2543.9   151.1 2542.43   175.5  2543.4   203.9 2540.36   240.4 2534.31
   275.8 2533.04   289.8 2535.15   301.2 2535.33  323.322531.801   333.6 2530.86
  349.152531.802   374.1 2534.89   390.3 2534.01   398.2 2535.21   402.7 2537.11
   411.2 2544.99   426.7 2552.96   476.2 2569.26   497.3  2579.8   501.1 2581.03
   522.5 2581.04   526.7 2582.67   535.3 2589.33   573.8 2600.99   601.8 2611.24
#Mann= 3 ,-1,0
       0      .1       0  323.32    .045       0  349.15      .1       0
#XS Ineff= 2 , 0
          297.18 2551.03
Permanent Ineff=
       F       F
Bank Sta=323.32,349.15
XS Rating Curve= 0 ,0
Exp/Cntr(USF)=0,0
Exp/Cntr=0.3,0.1

Type RM Length L Ch R = 1 ,9352    ,273.6,277,278.6
XS GIS Cut Line= 4
2186479.96430485607911.7369319472186538.34884325608175.771756049
2186622.30634743608348.0526284412186709.21008228608538.448070712
#Sta/Elev= 30
       0 2586.88    34.9 2582.52    46.5 2579.39    83.4 2573.27   162.4 2553.88
   185.8 2551.87     191 2549.91   198.1 2545.27   210.4 2533.02   218.6 2529.43
   263.1 2529.26   278.8 2531.63   338.5  2532.1   378.8  2529.9  389.862527.407
     401 2526.63  413.142527.407   445.5 2529.88   463.3 2536.12   480.9 2539.86
   494.5 2544.83   502.9 2546.14   520.5 2553.84   568.8 2570.53     582 2576.92
   591.1 2579.04   608.4 2580.29   617.2 2587.17   659.2 2603.44   671.4 2606.32
#Mann= 3 ,-1,0
       0      .1       0  389.86    .045       0  413.14      .1       0
#XS Ineff= 2 , 0
          295.16  2553.1
Permanent Ineff=
       F       F
Bank Sta=389.86,413.14
XS Rating Curve= 0 ,0
Exp/Cntr=0.3,0.1

Type RM Length L Ch R = 1 ,9075    ,184.7,185.2,185.5
XS GIS Cut Line= 5
2186227.92493776608031.7442972532186347.36056066608333.289681816
2186375.32968939608423.9774187222186383.76460131608458.454521398
2186456.61156583608627.410103276
#Sta/Elev= 30
       0 2582.15     5.8  2581.6    40.3 2573.62    83.3 2560.97   104.8 2556.35
   147.8 2543.93   173.6 2543.21   272.6 2534.32   285.5 2533.84   315.7 2528.33
   328.4 2524.54   403.8  2524.6   416.3 2523.61  426.022520.841   432.8 2519.27
   440.8 2519.16   449.3 2519.73  451.732520.839   453.4 2521.61   470.8 2536.54
   478.4 2541.47   492.5 2548.17   508.9  2554.5   540.5 2565.25   566.6 2567.61
     584 2576.37   587.1 2577.22   606.3 2577.45   618.9  2583.5   638.7 2589.65
#Mann= 3 ,-1,0
       0      .1       0  426.02    .045       0  451.73      .1       0
Bank Sta=426.02,451.73
XS Rating Curve= 0 ,0
Exp/Cntr(USF)=0,0
Exp/Cntr=0.3,0.1

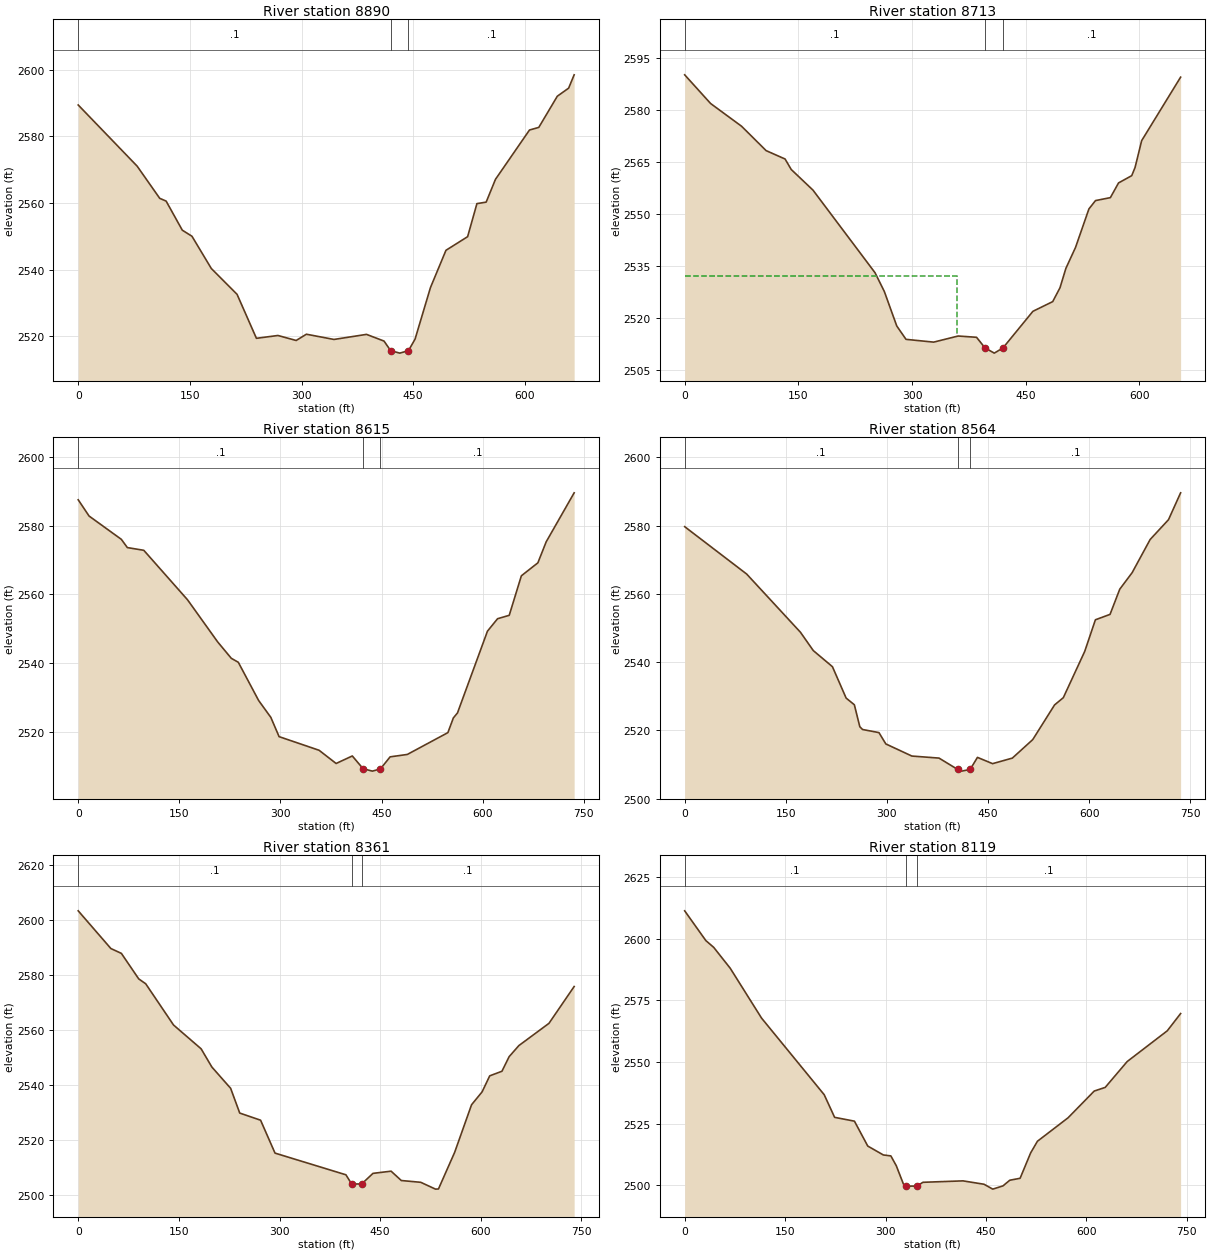
Type RM Length L Ch R = 1 ,8890    ,175.8,176.2,177.3
XS GIS Cut Line= 4
2186064.04155852608060.0835689382186157.37847496608284.696113263
2186201.75111131608489.6338343852186259.58163615608694.942246849
#Sta/Elev= 30
       0 2589.45    79.2 2571.07   109.5 2561.41   118.1 2560.58   139.8 2551.85
   152.8 2550.02   178.8 2540.33   213.4 2532.57   239.4 2519.36   268.3 2520.21
   292.8 2518.71   306.5 2520.59   343.6 2519.02   387.3 2520.54   410.8 2518.53
  419.722515.656     432 2514.91  443.652515.655   452.5 2519.12   473.2 2534.61
     494  2545.8   523.1 2549.89   535.6 2559.82     548 2560.27   560.5 2567.11
   606.2 2581.93   618.7 2582.72   643.6 2592.09   658.8 2594.51   666.2 2598.51
#Mann= 3 ,-1,0
       0      .1       0  419.72    .045       0  443.65      .1       0
Bank Sta=419.72,443.65
XS Rating Curve= 0 ,0
Exp/Cntr=0.3,0.1

Type RM Length L Ch R = 1 ,8713    ,108.1,98.9,96.3
XS GIS Cut Line= 4
2185940.80920791608071.7900476572186002.74041228608354.813980858
2186025.58336206608500.9062157582186110.48198692608700.519800092
#Sta/Elev= 30
       0  2590.1    34.2 2581.84    75.1 2575.28   107.5 2568.26   132.5 2565.85
   140.6 2562.83   169.3 2556.89   251.2 2533.09   263.5 2527.67   279.9 2517.74
   292.1 2513.89   328.6 2513.09   360.9 2514.85   385.2 2514.48  396.372511.424
   408.6 2509.92  420.092511.424   459.6 2521.97   485.7 2524.76   495.3 2528.75
   503.1 2534.35   515.8 2540.37   533.5 2551.47   542.2 2553.87   561.8 2554.72
   572.6 2558.96     590 2561.05   594.4 2563.42   603.1 2571.14   654.5 2589.43
#Mann= 3 ,-1,0
       0      .1       0  396.37    .045       0  420.09      .1       0
#XS Ineff= 2 , 0
          358.84 2532.07
Permanent Ineff=
       F       F
Bank Sta=396.37,420.09
XS Rating Curve= 0 ,0
Exp/Cntr(USF)=0,0
Exp/Cntr=0.3,0.1

Type RM Length L Ch R = 1 ,8615    ,47.6,50.7,51
XS GIS Cut Line= 6
2185874.08116156608081.2659096482185825.23080926608369.578773218
2185866.41836119608404.0613748412185939.21496462 608503.67777953
2185987.10746688608519.9612302962186069.58768461608718.091658071
#Sta/Elev= 30
       0 2587.58    16.1 2582.85      64 2576.05    72.9 2573.65    97.3 2572.86
   162.2 2558.43   206.8 2546.18   227.1 2541.38   237.5 2540.22   267.7 2529.07
   285.8 2524.15     298 2518.55   357.3 2514.58   382.6 2510.73   406.6 2512.92
   422.7 2509.18   436.5  2508.5   448.4 2509.16   462.7 2512.66   488.2 2513.36
   548.4 2519.72   556.5    2524   562.6 2525.45   607.1 2549.29   622.1 2552.92
   639.4 2553.91   657.4 2565.43   681.9 2569.21   694.2 2575.32   735.7 2589.61
#Mann= 3 ,-1,0
       0      .1       0   422.7    .045       0   448.4      .1       0
Bank Sta=422.7,448.4
XS Rating Curve= 0 ,0
Exp/Cntr(USF)=0,0
Exp/Cntr=0.3,0.1

Type RM Length L Ch R = 1 ,8564    ,199.2,203.3,203.6
XS GIS Cut Line= 6
2185838.05310187608105.0206742812185789.20274957608393.333537851
 2185830.3903015608427.8161394742185903.18690493608527.432544163
2185951.07940719608543.7159949292186033.55962492608741.846422704
#Sta/Elev= 30
       0 2579.69      92  2565.8   171.8 2548.73   190.8 2543.37   219.2 2538.65
   239.5 2529.45   251.7 2527.49   259.8 2521.06   263.9 2520.24   288.2 2519.33
   298.4 2516.01     337 2512.46   377.3 2511.86  404.982508.533   410.8 2508.04
  423.492508.531   434.3 2512.07   456.8 2510.23   486.1 2511.86   516.3 2517.27
   548.7 2527.44   561.7 2529.57   593.4 2543.11   609.3  2552.4     631 2553.98
   645.4 2561.36   663.8 2566.21   690.5 2575.93   717.7 2581.73   735.7 2589.61
#Mann= 3 ,-1,0
       0      .1       0  404.98    .045       0  423.49      .1       0
Bank Sta=404.98,423.49
XS Rating Curve= 0 ,0
Exp/Cntr(USF)=0,0
Exp/Cntr=0.3,0.1

Type RM Length L Ch R = 1 ,8361    ,245.6,242,241.2
XS GIS Cut Line= 4
 2185402.5930507   608240.5198952185627.52402113608426.258526412
2185732.41599332608655.462217007 2185850.9459803608810.680038261
#Sta/Elev= 30
       0 2603.24    48.7 2589.52    64.3 2587.77    90.2 2578.48   100.6  2576.7
   142.1  2561.7   183.2 2553.04   199.2 2546.42   227.2 2538.67   240.7 2529.68
   271.8 2527.08   293.3 2515.11     399 2507.22  407.472503.881   422.5  2503.9
   439.3 2507.74   466.3 2508.54   481.5 2505.14   510.5 2504.49   532.5 2502.01
   536.9 2502.07     561 2515.38   586.2  2532.7   601.9 2537.38   613.3 2543.22
   631.5 2544.89   642.2 2550.19   656.7 2554.22   701.6 2562.32   739.1 2575.71
#Mann= 3 ,-1,0
       0      .1       0  407.47    .045       0   422.5      .1       0
Bank Sta=407.47,422.5
XS Rating Curve= 0 ,0
Exp/Cntr=0.3,0.1

Type RM Length L Ch R = 1 ,8119    ,227.4,225.6,224
XS GIS Cut Line= 4
2185231.57495585608344.8454197532185444.43052142 608601.33637627
2185547.66547073608733.3068269262185737.10692409608880.177167172
#Sta/Elev= 30
       0 2611.35    31.6 2599.28    43.3 2596.54      68 2588.06   114.8 2567.82
   208.4 2536.72   223.9 2527.55   253.5    2526   273.4  2515.9   296.7 2512.28
   307.9  2511.9     316 2507.91   326.6 2500.52   330.2 2499.65  346.852499.654
   355.8 2501.19   415.6 2501.77     447  2500.4   460.1 2498.42   475.3 2499.73
   485.5 2502.03   500.9 2502.82   516.7 2513.15   526.8 2517.85   572.5 2527.36
   611.6 2538.22     628  2539.7   660.8 2550.19   720.7 2562.67   740.6 2569.67
#Mann= 3 ,-1,0
       0      .1       0   330.2    .045       0  346.85      .1       0
Bank Sta=330.2,346.85
XS Rating Curve= 0 ,0
Exp/Cntr(USF)=0,0
Exp/Cntr=0.3,0.1

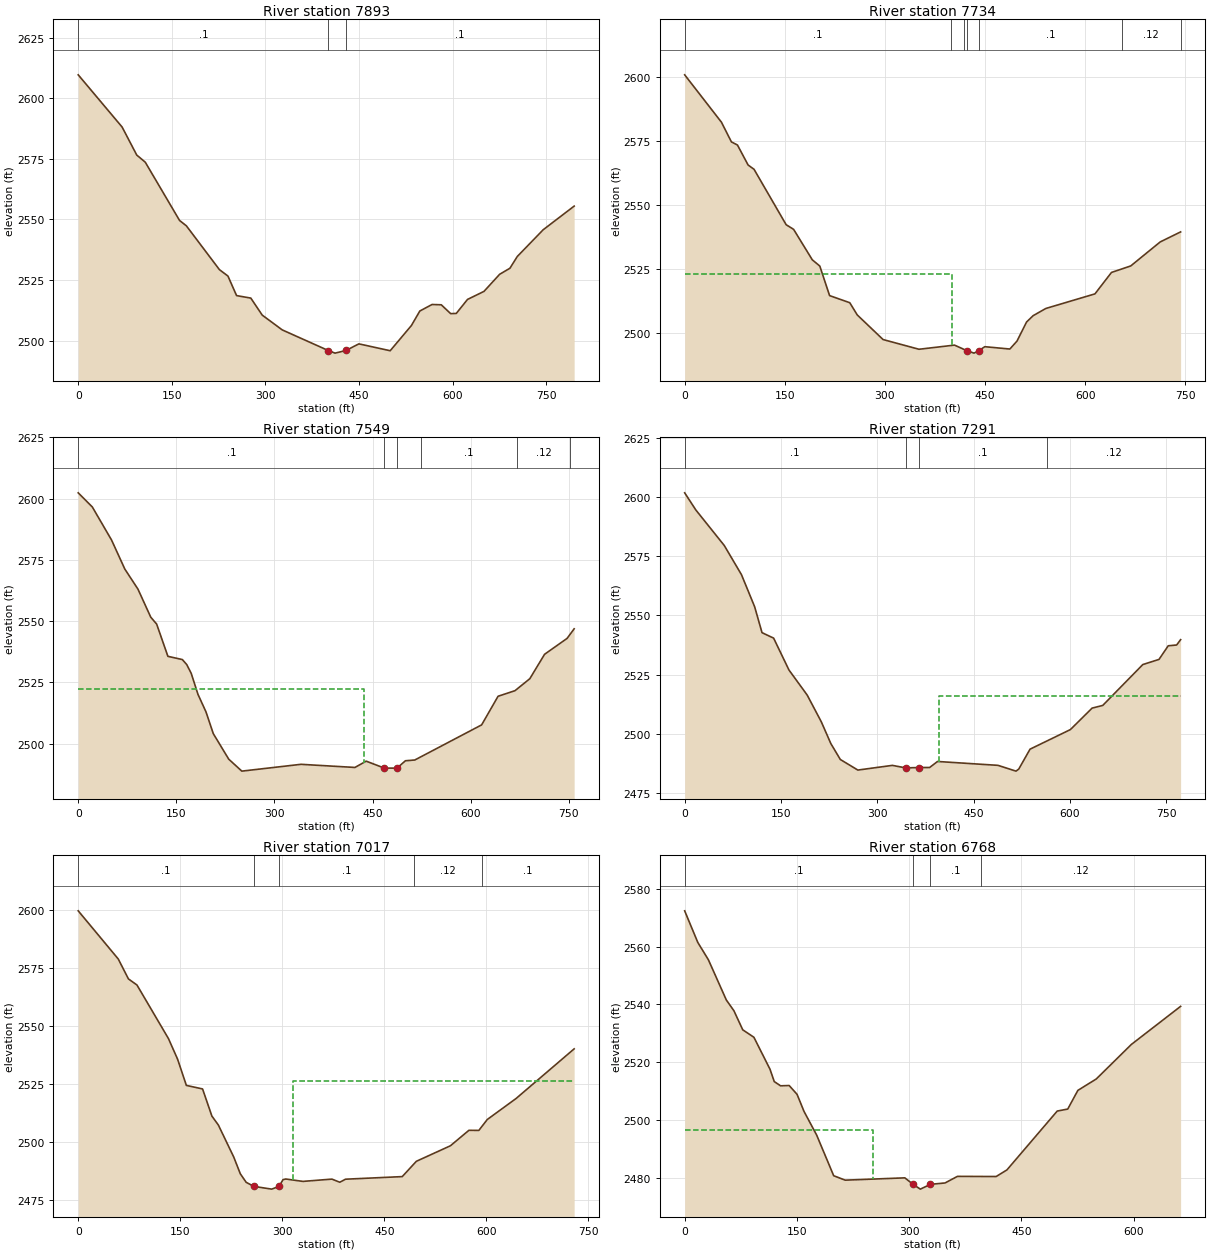
Type RM Length L Ch R = 1 ,7893    ,159.1,158.9,158.8
XS GIS Cut Line= 4
 2185074.6610067608431.0638143762185232.76679675 608717.27984734
2185377.22288778608840.9956171572185624.31929901608967.634345086
#Sta/Elev= 30
       0 2609.67    70.4 2588.11    93.8 2576.57   107.5 2573.61   162.4 2549.59
   173.4 2547.35   226.3 2529.29     240 2526.63   253.8 2518.58   276.6 2517.55
   294.9 2510.53     327 2504.42  400.832495.906   411.6 2494.84  429.152495.931
   449.8 2498.66     500 2495.83     534 2506.24   547.5 2512.22   567.1 2514.91
   581.9 2514.78   596.9 2511.13   605.9 2511.22   623.9    2517   650.3 2520.31
   675.4 2527.37   691.9 2529.87   703.7 2534.72   745.2 2545.75   794.8  2555.5
#Mann= 3 ,-1,0
       0      .1       0  400.83    .045       0  429.15      .1       0
Bank Sta=400.83,429.15
XS Rating Curve= 0 ,0
Exp/Cntr=0.3,0.1

Type RM Length L Ch R = 1 ,7734    ,185.3,184.9,184.1
XS GIS Cut Line= 4
2184883.78942745608602.567309471 2185089.5498075608804.780096766
2185262.00711323608950.8625403112185385.64327516609142.871481155
#Sta/Elev= 30
       0 2600.89    55.1 2582.38      70  2574.7    79.1 2573.47      95 2565.67
   103.9    2564     152 2542.36   163.2 2540.54   191.2 2528.64   202.4 2526.22
   217.1 2514.67   247.3  2511.9   258.5 2507.13   297.2 2497.51     351 2493.72
   404.2 2495.34  422.372493.202   433.5 2492.21  440.74  2493.2   449.6 2494.72
   487.1 2493.81   497.8 2496.91   512.1 2504.35     522 2506.84     541 2509.65
   614.6 2515.35   639.3 2523.71   668.2 2526.26   712.3 2535.63   742.9 2539.55
#Mann= 7 ,-1,0
       0      .1       0  398.49     .12       0  418.49      .1       0
  422.37    .045       0  440.74      .1       0   654.5     .12       0
  742.87      .1       0
#XS Ineff= 2 , 0
          400.87 2523.21
Permanent Ineff=
       F       F
Bank Sta=422.37,440.74
XS Rating Curve= 0 ,0
Exp/Cntr(USF)=0,0
Exp/Cntr=0.3,0.1

Type RM Length L Ch R = 1 ,7549    ,251.2,258.5,264.3
XS GIS Cut Line= 4
2184702.76106886608758.9902799052184867.14753186608879.675299524
2185145.99704202609086.9995345852185296.01186265609229.195848493
#Sta/Elev= 30
       0 2602.36    21.6 2596.57      51 2583.08    71.3 2571.22    91.3 2563.07
   110.9  2551.6   119.9 2548.79   137.1 2535.62   159.2  2534.3   165.9 2532.25
   172.7 2528.71     183 2520.14   195.3 2512.96   206.5 2504.06   230.1 2493.64
   250.1 2488.76   340.5 2491.54     423 2490.26   440.2 2492.83   467.9    2490
  487.312489.985   500.2 2492.99   514.5  2493.3   616.7 2507.64   641.8 2519.32
   667.7  2521.6   690.3 2526.48   712.9 2536.45   747.3 2542.94   758.1 2546.85
#Mann= 6 ,-1,0
       0      .1       0   467.9    .045       0  487.31     .12       0
  523.93      .1       0  671.41     .12       0  751.41      .1       0
#XS Ineff= 2 , 0
           436.1 2522.48
Permanent Ineff=
       F       F
Bank Sta=467.9,487.31
XS Rating Curve= 0 ,0
Exp/Cntr=0.3,0.1

Type RM Length L Ch R = 1 ,7291    ,285.3,273.4,257.7
XS GIS Cut Line= 4
2184601.58544783608924.2201215792184827.44648846609043.185097179
2184873.99800065609216.4601703362185181.75522014609356.114706909
#Sta/Elev= 30
       0  2601.8    17.4 2594.55    61.7 2579.54    88.5 2567.21     109 2553.66
   120.5 2542.71   138.6 2540.39   162.5 2526.92   190.9 2516.33   212.9 2505.02
   227.7 2495.85   242.5 2489.11   269.8 2484.64   323.6 2486.62   344.3 2485.56
   365.2 2485.71   381.6 2485.72     394 2488.27   488.2 2486.63   516.2 2484.19
   520.5 2485.05   538.1 2493.47     601 2501.75   634.8 2510.82   651.4 2511.96
   713.8 2529.23     739  2531.4   753.4 2537.16   766.5 2537.49   772.7 2539.75
#Mann= 4 ,-1,0
       0      .1       0   344.3    .045       0   365.2      .1       0
   564.7     .12       0
#XS Ineff= 2 , 0
                          396.82         2515.97
Permanent Ineff=
       F       F
Bank Sta=344.3,365.2
XS Rating Curve= 0 ,0
Exp/Cntr(USF)=0,0
Exp/Cntr=0.3,0.1

Type RM Length L Ch R = 1 ,7017    ,249.2,248.8,248.3
XS GIS Cut Line= 4
2184444.87090373609203.9256089752184658.79074714609324.189003524
2184896.12470275609394.4313401642185122.81588009609460.416565493
#Sta/Elev= 30
       0 2599.64    58.9 2578.86    73.8 2570.29    86.4 2567.64   132.6 2544.58
     146 2535.73     159 2524.36   182.8 2522.84   196.5 2511.14     206 2507.29
   228.6 2493.49   238.3 2486.25   246.9 2482.58  257.942480.834   284.4 2479.64
   295.22480.834   301.1 2483.74   305.2    2484   330.3 2482.97   372.9 2483.96
   384.5 2482.61   392.9 2483.92   476.3 2485.04   497.1 2491.65   547.1 2498.33
   574.3    2505   588.9 2504.96   601.3 2509.66   643.6 2518.71     729 2540.12
#Mann= 5 ,-1,0
       0      .1       0  257.94    .045       0   295.2      .1       0
  492.92     .12       0  592.92      .1       0
#XS Ineff= 2 , 0
                          315.38         2526.38
Permanent Ineff=
       F       F
Bank Sta=257.94,295.2
XS Rating Curve= 0 ,0
Exp/Cntr(USF)=0,0
Exp/Cntr=0.3,0.1

Type RM Length L Ch R = 1 ,6768    ,269.4,275.3,279.6
XS GIS Cut Line= 4
2184361.67108268609410.9896944942184518.42081837609543.961453207
2184748.78375574 609604.112850032184907.94124111 609754.57523579
#Sta/Elev= 30
       0 2572.34    17.5 2561.43    31.7 2555.41    55.7 2541.49    65.8 2537.79
    77.6  2531.2    92.5 2528.62     114 2517.58   119.7  2513.3   128.2 2511.83
   139.6 2511.94   150.2 2508.88   159.4 2503.02   176.4 2494.78   199.1 2480.75
   214.5 2479.21   294.2 2480.01  305.222477.768   314.9 2476.11  328.332477.767
   347.9 2478.24   364.5 2480.52   416.2 2480.47   430.6 2482.75   497.8  2503.1
   511.9  2503.8   525.4 2510.25     550  2514.2   596.9 2526.14   662.7 2539.31
#Mann= 4 ,-1,0
       0      .1       0  305.22    .045       0  328.33      .1       0
  395.55     .12       0
#XS Ineff= 2 , 0
          251.79 2496.54
Permanent Ineff=
       F       F
Bank Sta=305.22,328.33
XS Rating Curve= 0 ,0
Exp/Cntr(USF)=0,0
Exp/Cntr=0.3,0.1

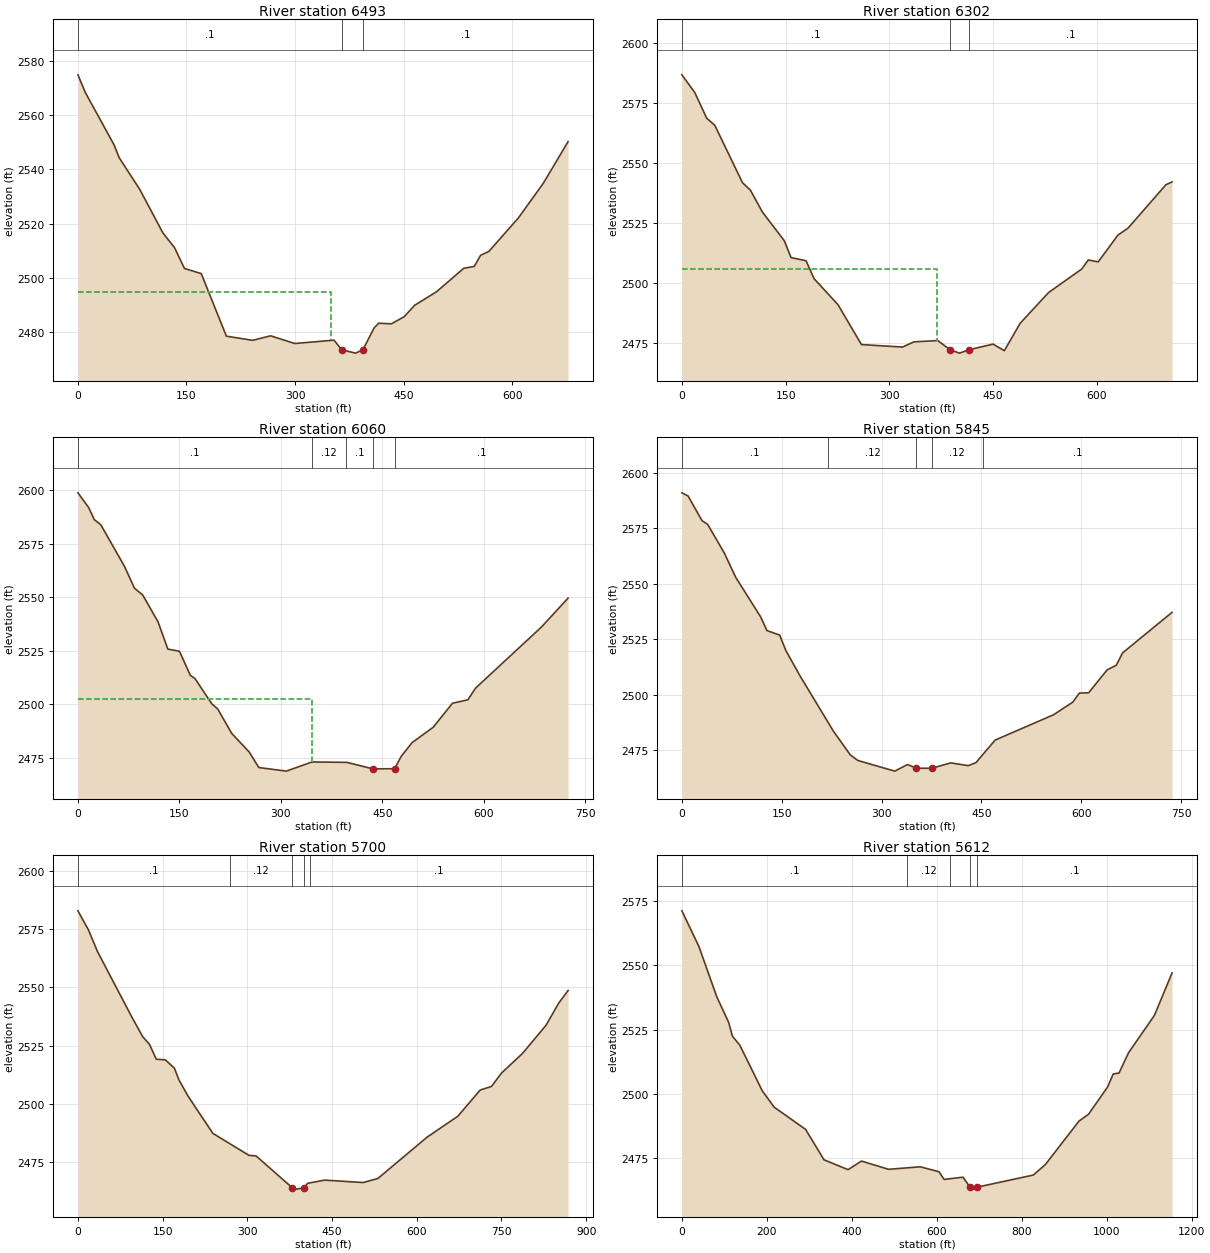
Type RM Length L Ch R = 1 ,6493    ,190.3,191.1,192.2
XS GIS Cut Line= 4
 2184227.7645547609529.3783048472184364.26749383609688.750597543
2184545.36443421609835.2630855832184742.92207023609961.471515532
#Sta/Elev= 30
       0 2574.73    10.3 2568.19    49.8 2549.02    56.9 2544.28    85.3 2532.61
   117.5  2516.5   133.5 2511.11   147.2 2503.45   170.4 2501.57   205.1 2478.54
   241.4    2477   266.3 2478.66   299.6 2475.83   353.8 2477.07  364.562473.498
   383.6 2472.29   393.72473.497   409.2 2481.55   415.5  2483.3   433.1 2483.08
   450.9 2485.71   465.1 2489.88   495.4 2494.87   533.1 2503.52   547.6  2504.2
   556.3 2508.28   567.8 2509.73   608.4    2522   643.2 2534.89   677.2 2550.14
#Mann= 3 ,-1,0
       0      .1       0  364.56    .045       0   393.7      .1       0
#XS Ineff= 2 , 0
          350.25 2494.76
Permanent Ineff=
       F       F
Bank Sta=364.56,393.7
XS Rating Curve= 0 ,0
Exp/Cntr=0.3,0.1

Type RM Length L Ch R = 1 ,6302    ,240,241.5,241.7
XS GIS Cut Line= 4
2184081.84648579609664.2674929422184260.96444422609837.638351103
 2184430.5039022609994.7257584982184621.42232951610120.342994998
#Sta/Elev= 30
       0 2586.77    18.6  2579.4    35.8 2568.72    47.6  2565.7    87.6 2541.79
    99.1 2538.64   116.3 2529.57     148 2517.61   157.9 2510.52   179.6  2509.2
   191.1 2501.75   225.8 2490.85   259.7 2474.23   319.2 2473.19   335.5 2475.36
   370.1  2475.9     3882472.021   401.6 2470.66   415.4 2472.07     450 2474.42
   466.4 2471.69   489.2  2483.1   530.3 2495.93   578.2 2505.73   587.7 2509.52
   602.1 2508.73   630.8 2519.95   645.2 2522.79     700 2540.91   708.9 2542.09
#Mann= 3 ,-1,0
       0      .1       0     388    .045       0   415.4      .1       0
#XS Ineff= 2 , 0
          368.52 2505.62
Permanent Ineff=
       F       F
Bank Sta=388,415.4
XS Rating Curve= 0 ,0
Exp/Cntr(USF)=0,0
Exp/Cntr=0.3,0.1

Type RM Length L Ch R = 1 ,6060    ,214.1,215.9,219.8
XS GIS Cut Line= 4
2183953.53447195609781.9150054612184105.54458788 609987.91445358
2184263.06903078610149.9274093462184455.88070605 610296.83111465
#Sta/Elev= 30
       0 2598.62    15.7 2591.86    24.2 2586.14    33.9 2583.71    68.7 2564.41
    83.6 2554.17    95.8    2551   118.4  2538.5   132.9  2525.8   150.1 2524.77
   166.1  2513.6     173 2512.06   197.9 2500.29   206.5 2497.95   227.3 2486.52
   253.1 2477.87   267.3 2470.61     308 2468.93   345.9 2473.19   397.5 2473.02
   436.3 2469.96   468.1 2470.07   477.8 2475.83   493.9 2482.22     525 2489.36
   553.6 2500.57   576.3 2502.16   587.8 2507.65   684.9 2536.03   724.4 2549.55
#Mann= 5 ,-1,0
       0      .1       0  346.01     .12       0  396.01      .1       0
   436.3    .045       0   468.1      .1       0
#XS Ineff= 2 , 0
          345.42 2502.72
Permanent Ineff=
       F       F
Bank Sta=436.3,468.1
XS Rating Curve= 0 ,0
Exp/Cntr=0.3,0.1

Type RM Length L Ch R = 1 ,5845    ,147,144.9,142.5
XS GIS Cut Line= 4
  2183904.008188609852.4352801322183997.85432664610142.737782351
2184094.70360897610253.4226764512184340.55178721610396.035905386
#Sta/Elev= 30
       0 2590.92     9.2 2589.52    30.2 2578.38    38.6 2576.74    63.8 2563.77
    80.7 2552.93   118.3 2535.01   127.8 2528.84   146.9  2526.8   156.3 2519.79
   177.3  2508.5   227.8 2483.43     253 2472.83   264.4 2470.29   319.8  2465.5
     339 2468.47  352.352466.797   375.4  2466.8     404 2469.22   430.1 2467.97
   441.7  2469.3   470.6 2479.49   558.4  2490.9   587.2 2496.58   597.2 2500.68
   611.1 2500.81   638.8  2511.1   652.7 2513.24     662 2518.76   736.4 2537.06
#Mann= 5 ,-1,0
       0      .1       0     220     .12       0  352.35    .045       0
   375.4     .12       0  452.17      .1       0
Bank Sta=352.35,375.4
XS Rating Curve= 0 ,0
Exp/Cntr(USF)=0,0
Exp/Cntr=0.3,0.1

Type RM Length L Ch R = 1 ,5700    ,92,88,83.6
XS GIS Cut Line= 4
2183810.72971572609890.6353159252183827.45972511610190.488561161
2184053.95831379 610338.484798082184319.06461644610472.324873207
#Sta/Elev= 30
       0 2582.84    18.6  2574.7    34.6 2565.42    94.7 2537.65   114.7  2528.9
   126.7 2525.62   138.8 2519.23   154.8 2518.97   170.8 2515.42   178.8 2510.42
   194.8 2503.49   238.9 2487.47   302.8 2478.05   315.5 2477.79  379.512464.159
   387.2 2463.56   400.3 2464.15   406.8 2466.06   436.9 2467.42   505.1 2466.38
   531.1 2468.12   618.2 2485.81   672.8 2494.82   712.3 2506.03   732.4 2507.59
   750.2 2513.35     787 2521.66   828.8 2533.76   851.2 2543.23   867.9  2548.7
#Mann= 5 ,-1,0
       0      .1       0     270     .12       0  379.51    .045       0
   400.3     .12       0  410.32      .1       0
Bank Sta=379.51,400.3
XS Rating Curve= 0 ,0
Exp/Cntr(USF)=0,0
Exp/Cntr=0.3,0.1

Type RM Length L Ch R = 1 ,5612    ,124.3,123.9,123.4
XS GIS Cut Line= 4
2183233.58196905610429.5639501312183500.46663933610270.673968673
2184052.77357162610346.652593735 2184307.4574246610475.895701858
#Sta/Elev= 30
       0 2571.22    40.1 2557.34    82.2 2537.77   110.1 2527.85   118.9 2522.49
   136.4 2518.98   189.2 2501.25   217.2 2494.91   291.1 2486.28   334.5 2474.45
   391.1 2470.62   422.6 2473.96   486.5 2470.75     561 2471.73   605.1 2469.81
   617.2 2466.82   661.6 2467.69   678.2 2463.84   685.8 2463.05  695.732463.845
   827.1 2468.52   855.4 2472.58   934.7  2489.5   957.2 2492.16    1002 2502.75
  1015.3 2507.82  1028.9 2508.16  1051.3 2516.04  1112.4 2530.64  1153.7 2547.08
#Mann= 5 ,-1,0
       0      .1       0   530.6     .12       0   630.6      .1       0
   678.2    .045       0  695.73      .1       0
Bank Sta=678.2,695.73
XS Rating Curve= 0 ,0
Exp/Cntr(USF)=0,0
Exp/Cntr=0.3,0.1

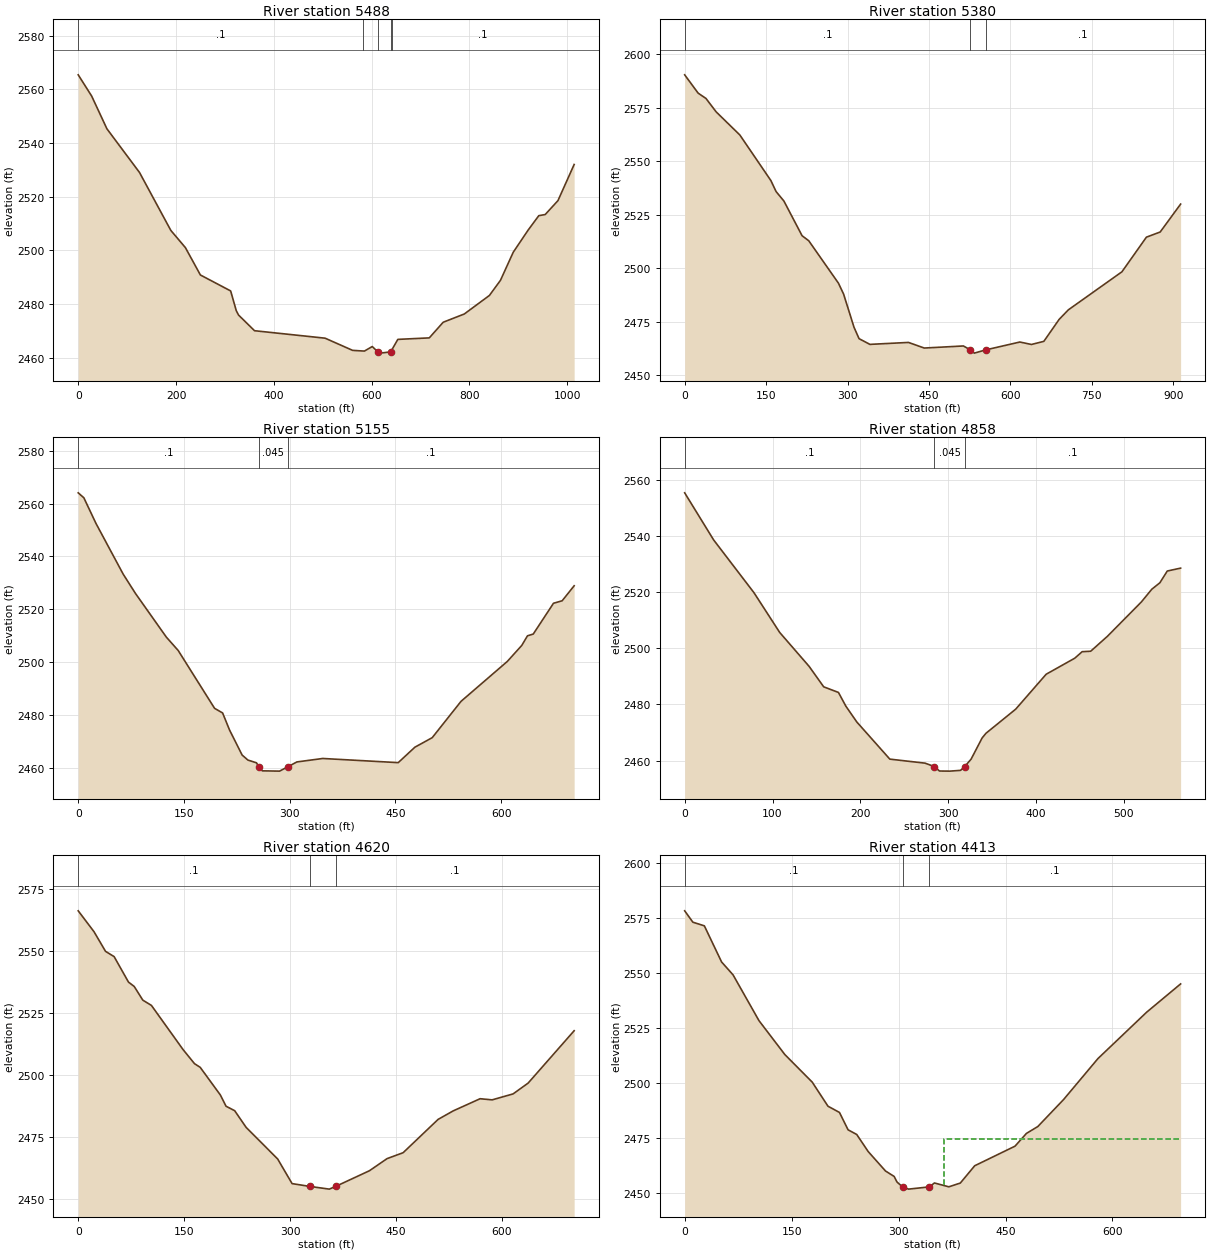
Type RM Length L Ch R = 1 ,5488    ,109.6,108.2,107.9
XS GIS Cut Line= 4
2183278.11175265610575.5155706162183544.45703715610412.678621102
2183977.03492803610456.872045429 2184222.5601397610562.434141234
#Sta/Elev= 30
       0 2565.36    27.5 2557.45    58.7 2545.25   125.4 2528.97   189.4 2507.39
   219.2 2500.98   249.9 2490.78   311.8 2484.83   323.3 2477.46     328 2475.84
   360.6 2470.01   504.9 2467.23   561.2 2462.69   585.3 2462.42   601.4 2464.12
612.93922462.103   617.5 2461.66 639.0772462.121   653.7 2466.78     718 2467.34
   746.5 2473.17   789.6 2476.24     841 2483.15   863.6 2488.79   889.7 2499.24
   919.9 2507.43     942 2512.88   955.1  2513.3   981.2 2518.49  1014.3 2531.95
#Mann= 5 ,-1,0
       0      .1       0  582.18     .12       0612.9392    .045       0
 639.077     .12       0  642.18      .1       0
Bank Sta=612.9392,639.077
XS Rating Curve= 0 ,0
Exp/Cntr(USF)=0,0
Exp/Cntr=0.3,0.1

Type RM Length L Ch R = 1 ,5380    ,224.3,224.8,203.4
XS GIS Cut Line= 4
2183339.42114635610712.9346187582183606.67720533610537.370672488
2183971.84033813610556.8693585932184187.78504889610630.801332131
#Sta/Elev= 30
       0 2590.48    24.8 2581.92    39.2 2579.44    58.1 2573.14   101.6 2562.37
   158.8 2541.05   168.4  2535.9   182.8 2531.48   216.3 2515.25   228.6  2512.9
   283.3 2493.07   292.8 2487.96     312 2472.43   321.3 2467.11   341.3 2464.45
   412.3 2465.36   441.4 2462.74   513.5 2463.71  526.432461.865   533.6 2460.36
  554.412461.864   617.6 2465.55   638.9 2464.41   661.7 2465.86     690 2476.17
   706.9  2480.6   805.6 2498.39   850.7 2514.58   876.1    2517   913.7 2530.04
#Mann= 3 ,-1,0
       0      .1       0  526.43    .045       0  554.41      .1       0
Bank Sta=526.43,554.41
XS Rating Curve= 0 ,0
Exp/Cntr=0.3,0.1

Type RM Length L Ch R = 1 ,5155    ,282.6,297,282.1
XS GIS Cut Line= 4
2183503.79583133610864.0548294292183687.91589555610722.505878321
2183922.05701768610674.6133760672184148.74819502610724.634433977
#Sta/Elev= 30
       0 2564.04       8 2562.17    25.1 2552.52    63.8  2533.3    81.2 2526.01
     125  2509.5   141.8 2504.45   193.4 2482.59   204.8 2480.84   214.7 2474.36
   232.5 2464.92   240.7 2463.03   252.9 2461.99  256.192460.446   261.1 2458.96
   285.6 2458.85  296.962460.446   310.1 2462.32   346.8 2463.63   453.9 2462.06
   477.5 2467.89   502.1  2471.5     543 2485.24   608.6 2500.31   629.1 2506.36
   637.2 2509.99   645.4 2510.66   674.1  2522.3   686.4 2523.24   703.4 2528.91
#Mann= 3 ,-1,0
       0      .1       0  256.19    .045       0  296.96      .1       0
Bank Sta=256.19,296.96
XS Rating Curve= 0 ,0
Exp/Cntr(USF)=0,0
Exp/Cntr=0.3,0.1

Type RM Length L Ch R = 1 ,4858    ,238,238.1,235.5
XS GIS Cut Line= 4
2183612.59569982610999.0589336512183834.51931873610931.700405691
2183925.90937117610921.7066157042184154.58030018610846.252695311
#Sta/Elev= 30
       0  2555.5      33 2538.69      79 2519.83   108.2 2505.69   141.7 2493.59
   158.3 2486.29   175.1 2484.29   183.5 2479.41     196 2473.75   233.6  2460.5
   273.8 2459.06  284.332457.835   290.1 2456.26     302 2456.22   314.1 2456.49
  318.792457.835   326.1 2460.47   338.7 2468.06   343.1 2469.73   376.9 2478.32
   411.6 2490.78   444.2 2496.51   452.6 2498.83   462.3 2498.99   481.3  2504.3
     520 2516.57   531.9 2521.11   541.1 2523.42   549.5  2527.6   564.7 2528.64
#Mann= 3 ,-1,0
       0      .1       0  284.33    .045       0  318.79      .1       0
Bank Sta=284.33,318.79
XS Rating Curve= 0 ,0
Exp/Cntr=0.3,0.1

Type RM Length L Ch R = 1 ,4620    ,205.4,206.2,206.8
XS GIS Cut Line= 4
2183554.09468889  611217.20088032183851.45538088611163.770827096
2183972.78305325611142.4852705382184233.53112109611048.828821685
#Sta/Elev= 30
       0 2566.28    22.4 2557.84    38.7 2549.92    50.9 2547.78    71.2 2537.51
    79.3 2535.75    91.5 2530.22   103.7 2528.09   148.4  2510.3   164.7 2504.58
   172.8 2503.08   201.3 2491.94   209.4 2487.38   221.6 2485.59   237.8 2478.86
   282.5 2466.09   302.9 2456.15327.72712455.028   355.6 2453.92364.80712455.034
   412.5 2461.35   437.4 2466.23   460.2 2468.63   509.7 2482.07   530.9 2485.48
   569.2 2490.42   586.2 2489.96   615.9 2492.36   637.2 2496.72   702.4 2517.87
#Mann= 3 ,-1,0
       0      .1       0327.7271    .045       0364.8071      .1       0
Bank Sta=327.7271,364.8071
XS Rating Curve= 0 ,0
Exp/Cntr(USF)=0,0
Exp/Cntr=0.3,0.1

Type RM Length L Ch R = 1 ,4413    ,262.5,266.3,266.4
XS GIS Cut Line= 4
2183600.78746303611401.8392473592183879.09348781611366.244869919
2184055.69799863611342.0834857572184291.65542837 611361.46934991
#Sta/Elev= 30
       0 2578.11    11.5 2572.94    27.6 2571.28    51.8 2554.84    67.9 2548.97
   104.2 2528.17   140.5 2512.74   178.9  2500.2     201 2489.25   217.1 2486.41
   229.2 2478.51   241.3  2476.4   257.4 2468.63   281.7 2459.78   293.8 2457.31
   297.8 2454.77  305.532452.566     314 2451.54  343.332452.568   350.3 2454.34
   370.5 2452.59   386.6  2454.3   406.8 2462.17   463.3 2471.07   479.4 2476.89
   495.3    2480   531.5  2492.3   579.7 2510.93   647.9 2531.99   695.6 2544.87
#Mann= 3 ,-1,0
       0      .1       0  305.53    .045       0  343.33      .1       0
#XS Ineff= 2 , 0
                          363.39         2474.44
Permanent Ineff=
       F       F
Bank Sta=305.53,343.33
XS Rating Curve= 0 ,0
Exp/Cntr=0.3,0.1