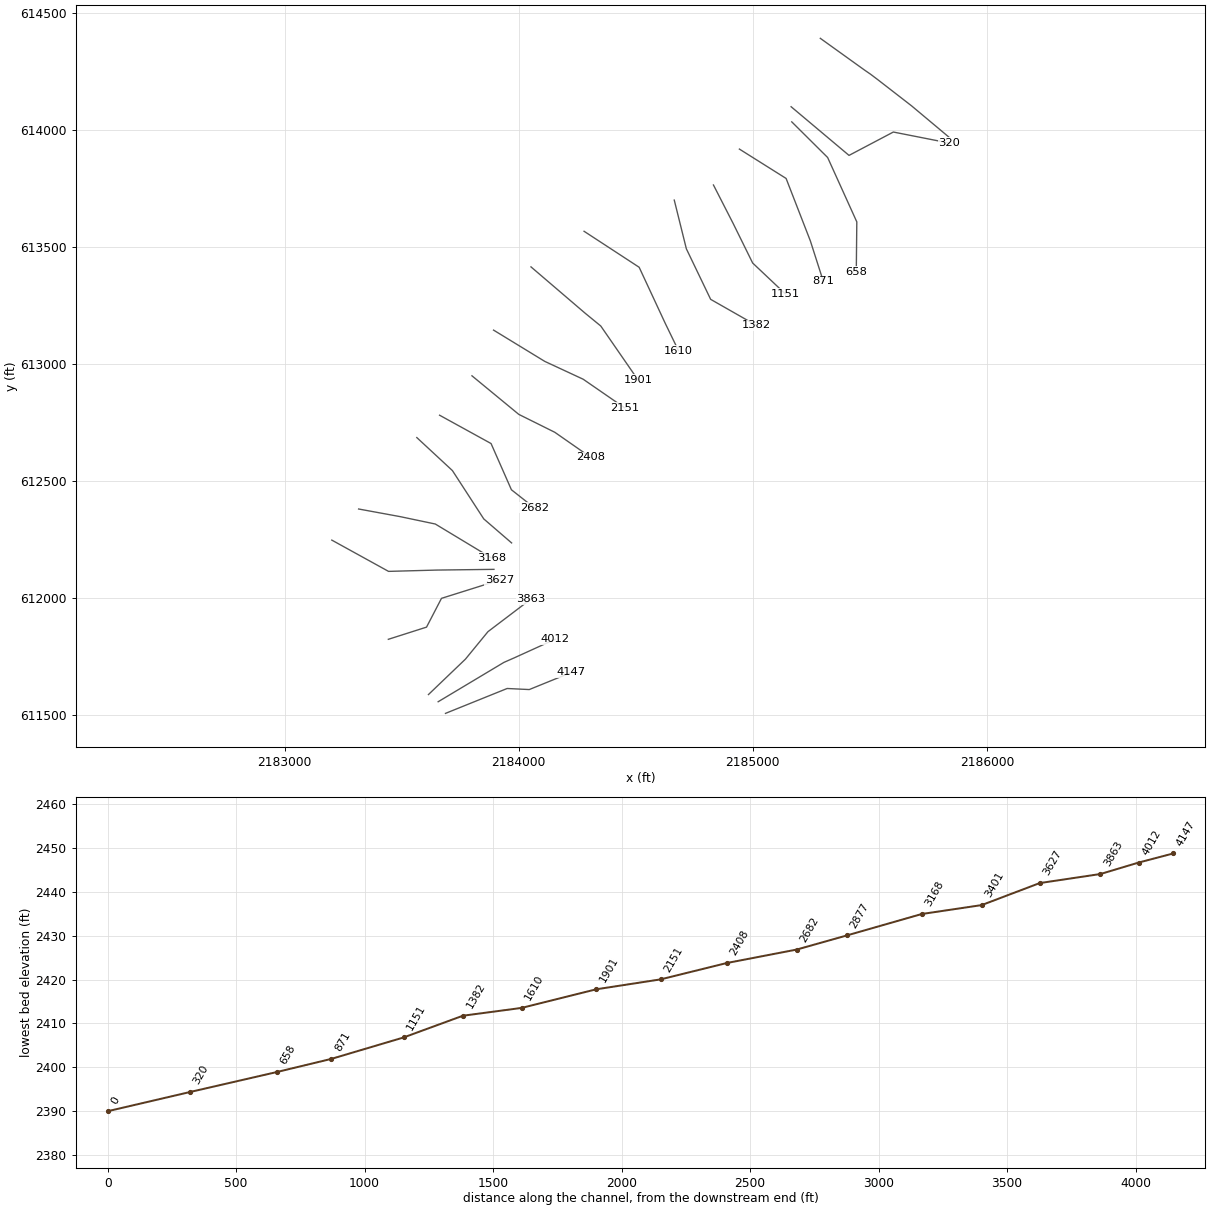
HEC-RAS study MARSHFK.prj: MARSHFK

--- MARSHFK.g01 (geometry) --- (continued)

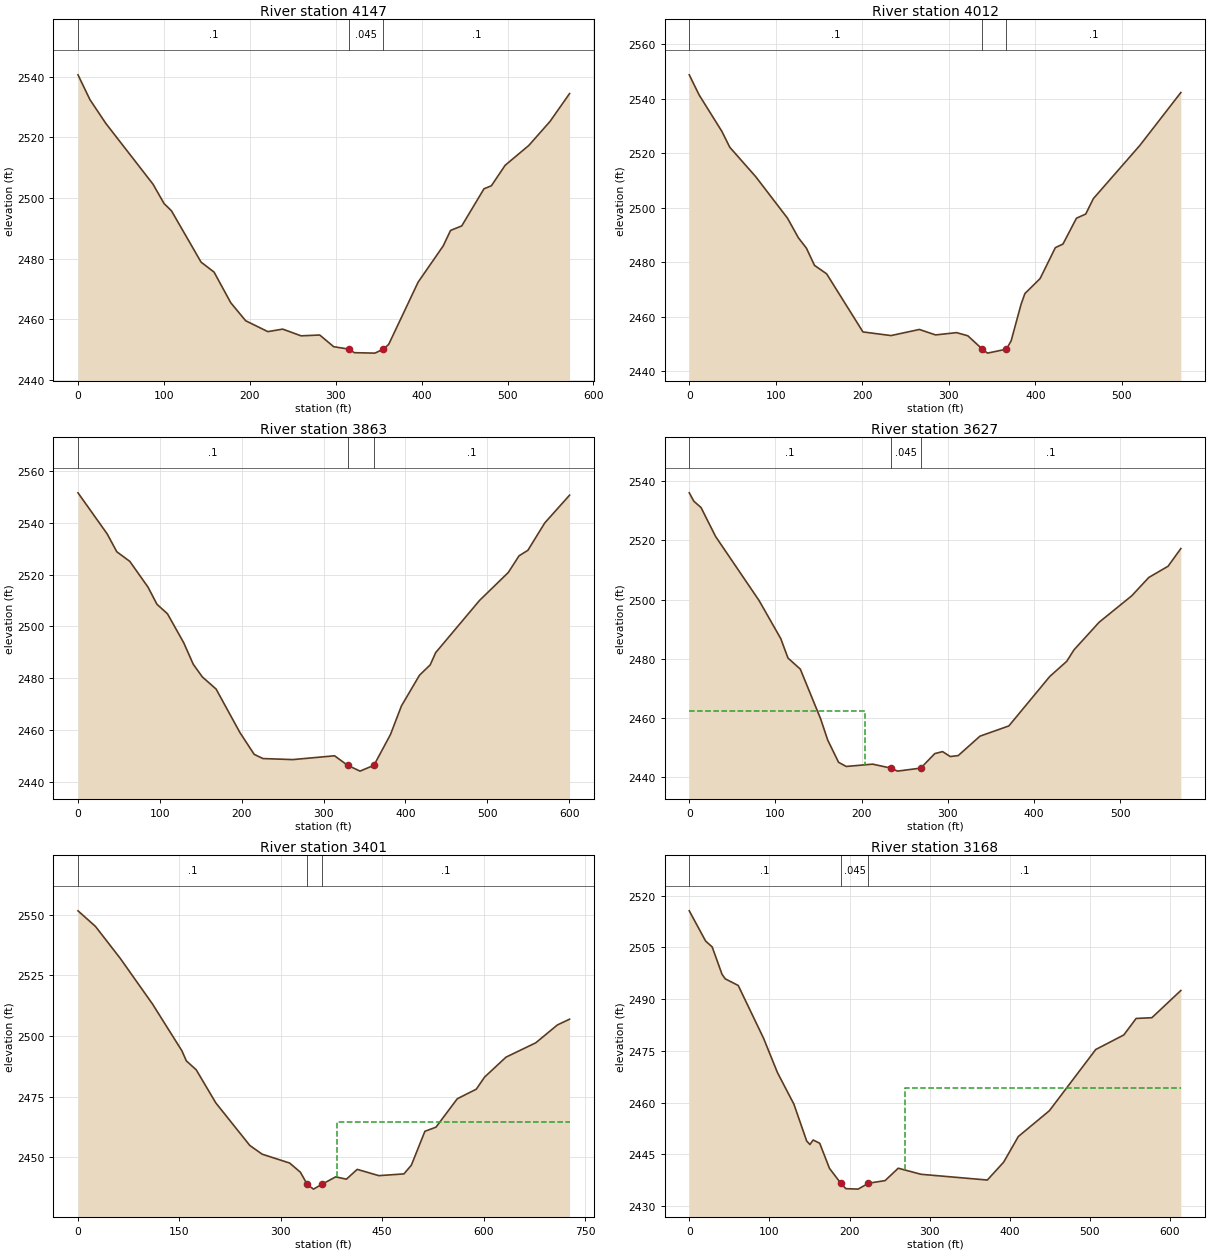
Type RM Length L Ch R = 1 ,4147    ,123.5,135.5,141.3
XS GIS Cut Line= 4
 2183687.2593234611507.962471995 2183950.6680858   611614.283827
2184045.07868019611609.7032536982184224.38293969611682.641109547
#Sta/Elev= 30
       0 2540.66    13.9 2532.47    32.4 2524.62    87.3 2504.56   100.2 2498.15
   108.8 2495.76   143.3  2478.8   158.4 2475.52   177.8 2465.41   195.2 2459.45
     221 2455.86   238.3 2456.69   259.7 2454.47   281.4 2454.74   297.6 2450.89
  315.582450.069   321.6 2448.91   345.6 2448.76  355.552450.071   361.7 2451.67
   395.9 2472.19   425.1 2484.16   433.7 2489.28   446.7 2490.77   472.6 2503.03
   481.2 2504.03   497.2 2510.78   524.8 2517.35   549.4 2525.25   572.2 2534.47
#Mann= 3 ,-1,0
       0      .1       0  315.58    .045       0  355.55      .1       0
Bank Sta=315.58,355.55
XS Rating Curve= 0 ,0
Exp/Cntr(USF)=0,0
Exp/Cntr=0.3,0.1

Type RM Length L Ch R = 1 ,4012    ,142.5,148.5,155.7
XS GIS Cut Line= 4
2183655.98032285611557.6966567392183936.94966941611725.852553545
2183980.58506035611745.0095544472184156.19090195611824.830391538
#Sta/Elev= 30
       0 2548.77    11.4 2541.39    37.7 2528.02    46.8 2522.21    76.9 2511.36
   113.5 2496.19   126.1 2488.98   135.4 2485.17   144.7 2478.87   158.7 2475.77
   200.7 2454.45   233.1 2453.11   265.9 2455.35   284.6 2453.35   308.9 2454.19
   321.9 2453.03   338.7 2448.12   344.6 2446.67  366.462448.121   371.9 2451.17
   383.4 2464.59   387.8 2468.51   405.4 2474.03     423 2485.37   431.8 2486.69
   447.4 2496.17   458.1  2497.7   466.9 2503.34   520.5 2522.82     568 2542.27
#Mann= 3 ,-1,0
       0      .1       0   338.7    .045       0  366.46      .1       0
Bank Sta=338.7,366.46
XS Rating Curve= 0 ,0
Exp/Cntr(USF)=0,0
Exp/Cntr=0.3,0.1

Type RM Length L Ch R = 1 ,3863    ,233.5,236.5,240.2
XS GIS Cut Line= 4
2183614.45548779611588.3722032472183772.49211008611739.702906889
2183868.66050407611857.0325121922184051.82391872611995.946528458
#Sta/Elev= 30
       0 2551.69    35.7 2535.78    47.4  2528.9    63.3 2525.18    85.5 2515.23
    96.5 2508.57   109.3 2504.91   129.1 2493.73   140.8 2485.38   151.9 2480.48
   168.7  2475.8   197.8 2458.97   215.2 2450.55   225.9 2448.92   262.3 2448.52
   313.4 2449.99  329.182446.336   344.5 2444.06  361.512446.338   381.7 2458.24
     395 2469.25   417.1 2481.15   430.2 2485.16   436.9  2489.9   490.4 2510.06
   525.5 2520.86   538.7 2527.33   549.5 2529.46   570.1 2540.05   600.4 2550.78
#Mann= 3 ,-1,0
       0      .1       0  329.18    .045       0  361.51      .1       0
Bank Sta=329.18,361.51
XS Rating Curve= 0 ,0
Exp/Cntr=0.3,0.1

Type RM Length L Ch R = 1 ,3627    ,240.1,225.8,211
XS GIS Cut Line= 4
2183443.09058445 611824.392795622183606.27985139611876.424156094
2183670.13652107611999.4073717612183918.46801424612077.454412472
#Sta/Elev= 30
       0 2536.08     5.3 2533.25    13.7 2531.09    30.5 2521.34    80.9  2499.7
   106.1 2486.82   114.5 2480.22   128.8 2476.48   152.3 2459.73   160.6 2452.49
   173.2 2444.97   182.1 2443.57   212.7 2444.35  233.862443.016   241.5 2441.99
  268.512443.016   284.8 2447.92   293.8 2448.59   302.8 2446.92     312 2447.25
   337.2 2453.81   370.7 2457.27   418.2    2474   437.8  2479.1   446.2 2482.97
   475.5 2492.35   513.3 2501.28     533 2507.46   555.4 2511.26   570.2 2517.24
#Mann= 3 ,-1,0
       0      .1       0  233.86    .045       0  268.51      .1       0
#XS Ineff= 2 , 0
          204.37 2462.16
Permanent Ineff=
       F       F
Bank Sta=233.86,268.51
XS Rating Curve= 0 ,0
Exp/Cntr(USF)=0,0
Exp/Cntr=0.3,0.1

Type RM Length L Ch R = 1 ,3401    ,233.7,232.9,227
XS GIS Cut Line= 4
2183201.57669531612248.1580708592183443.96742837612114.558123679
2183650.51688941612120.1812498242183894.20729824 612123.21495531
#Sta/Elev= 30
       0 2551.55    25.8 2545.15    62.3 2532.06   110.1 2513.23   153.7 2493.93
   160.2  2489.8   174.9 2486.09   203.9 2472.46   254.2 2454.94   272.4 2451.36
     313 2447.72     329 2443.93  339.032438.943   348.3 2436.97  360.752438.942
   381.2 2442.03     397 2441.06     413 2445.11     445 2442.52   482.1 2443.24
   493.1 2446.83   513.1 2460.77   529.5 2462.48     561 2474.17   589.1 2478.12
   601.5 2483.13   633.1 2491.31   677.1 2497.21   709.1 2504.57   727.1 2506.93
#Mann= 3 ,-1,0
       0      .1       0  339.03    .045       0  360.75      .1       0
#XS Ineff= 2 , 0
                          382.77         2464.45
Permanent Ineff=
       F       F
Bank Sta=339.03,360.75
XS Rating Curve= 0 ,0
Exp/Cntr=0.3,0.1

Type RM Length L Ch R = 1 ,3168    ,304.5,290.5,276.9
XS GIS Cut Line= 4
 2183316.0753867612381.0845839652183493.27764505612348.517682432
2183643.66010213612316.9086309432183883.05262223612172.370685355
#Sta/Elev= 30
       0 2515.62    20.4 2506.86    28.6 2505.15    40.8 2497.28    44.8 2495.92
    61.1 2493.98    92.8 2478.64   110.1 2468.71   130.6 2459.57   146.5 2448.91
   150.6 2447.88   154.6 2449.18   162.8 2448.24     175 2440.96  189.092436.656
   195.4 2435.08   210.7 2434.94  223.672436.653   244.4 2437.41   260.8    2441
   289.4 2439.24     372 2437.58   392.3 2442.74   410.7  2450.2   449.4 2457.66
   507.3 2475.42   542.3 2479.63   557.7 2484.42   577.4 2484.64   613.5 2492.53
#Mann= 3 ,-1,0
       0      .1       0  189.09    .045       0  223.67      .1       0
#XS Ineff= 2 , 0
                          268.88         2464.31
Permanent Ineff=
       F       F
Bank Sta=189.09,223.67
XS Rating Curve= 0 ,0
Exp/Cntr(USF)=0,0
Exp/Cntr=0.3,0.1

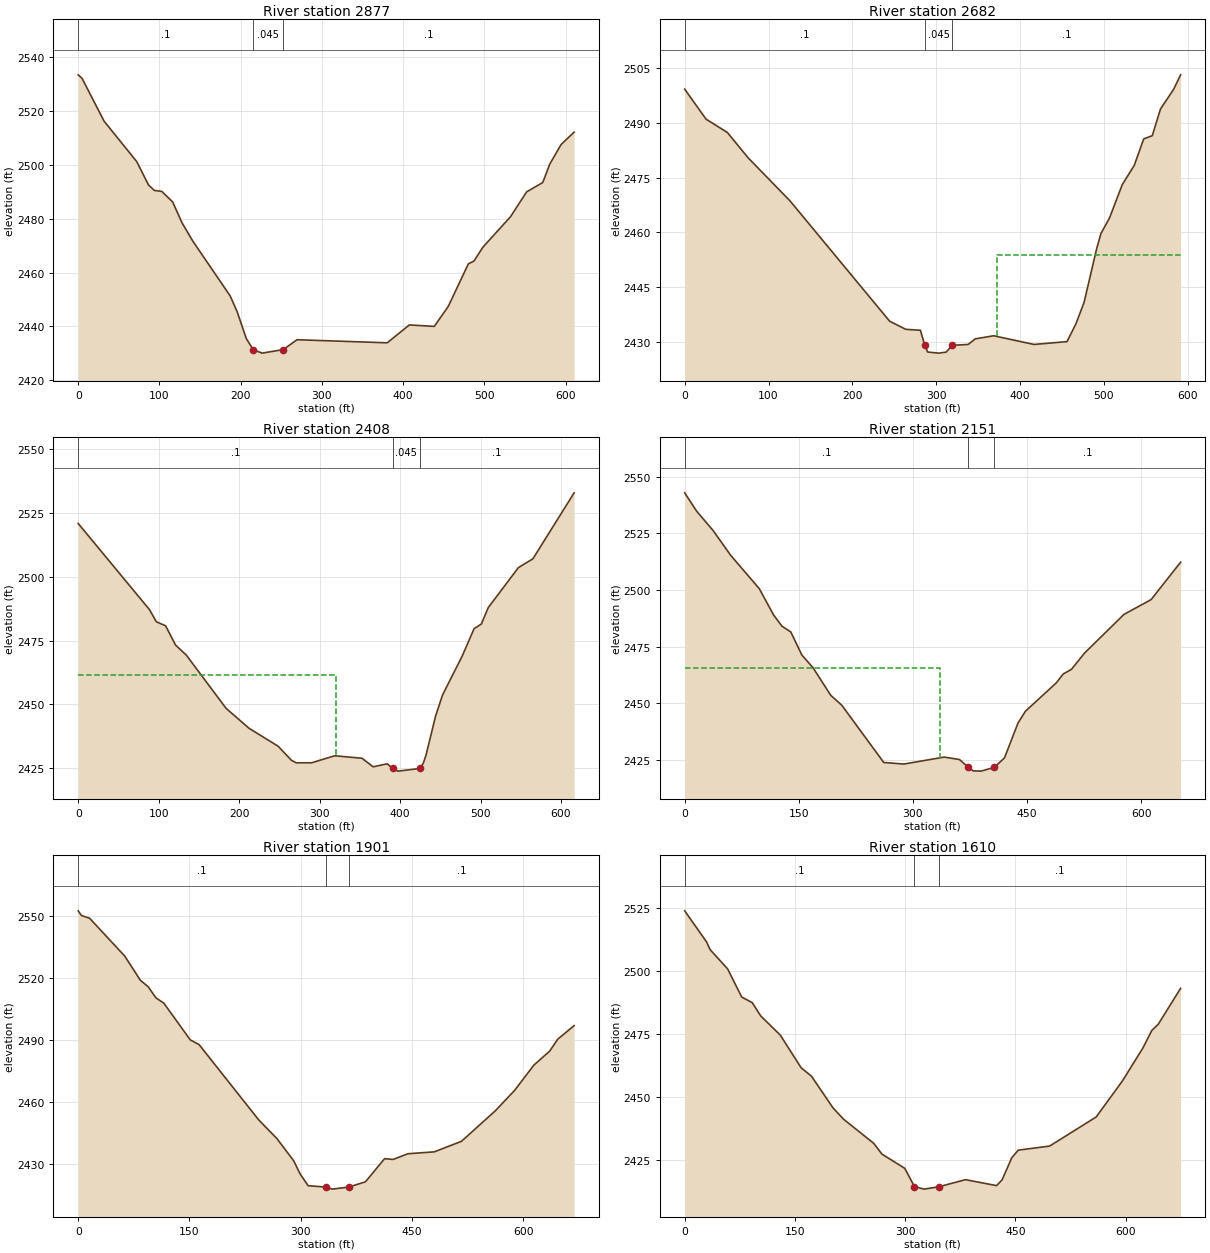
Type RM Length L Ch R = 1 ,2877    ,197.3,195.5,191.6
XS GIS Cut Line= 4
2183564.75305832612686.1784344232183716.85768995612545.124253267
2183850.71138949 612338.728870072183969.64154122612236.136833484
#Sta/Elev= 30
       0 2533.44     4.7 2532.15    31.9 2516.21    72.1 2501.19    86.5 2492.55
    93.7  2490.5   102.9 2490.14   116.3 2486.21   127.7 2478.52     141 2471.71
   187.1  2451.3   195.6  2445.5   206.9 2435.48  215.342431.379   226.4 2430.07
  252.372431.378   269.4 2435.05   380.4  2433.9   407.6 2440.54   438.3    2440
   455.6 2447.45   480.3 2463.26   487.1 2464.25   498.1 2469.39   532.2 2480.75
     552 2489.96   571.9 2493.46   580.4 2500.24   594.5 2507.58   610.5 2512.16
#Mann= 3 ,-1,0
       0      .1       0  215.34    .045       0  252.37      .1       0
Bank Sta=215.34,252.37
XS Rating Curve= 0 ,0
Exp/Cntr=0.3,0.1

Type RM Length L Ch R = 1 ,2682    ,265.3,273.5,288
XS GIS Cut Line= 4
2183662.01802965612781.7103600912183881.91622382612660.698029291
2183968.82527042612463.2988861232184066.73883058612386.042437101
#Sta/Elev= 30
       0 2499.31    25.5 2491.07    50.9 2487.42    75.6 2480.48   125.6 2468.64
   244.4 2435.61   263.6 2433.38   281.1 2433.11  286.292428.998   289.8 2427.14
   302.9 2426.84   311.7 2427.11  319.292428.996   337.9 2429.21   346.6 2430.76
   368.5 2431.61   416.6 2429.22   455.9    2430   466.7 2434.95   476.3 2440.79
   491.3 2455.53   496.4 2459.68   506.6 2463.94   521.8 2473.09   536.1 2478.38
   547.4 2485.65   557.6 2486.53   567.4 2493.86     583 2499.24   591.4 2503.24
#Mann= 3 ,-1,0
       0      .1       0  286.29    .045       0  319.29      .1       0
#XS Ineff= 2 , 0
                          372.13         2453.79
Permanent Ineff=
       F       F
Bank Sta=286.29,319.29
XS Rating Curve= 0 ,0
Exp/Cntr(USF)=0,0
Exp/Cntr=0.3,0.1

Type RM Length L Ch R = 1 ,2408    ,256.4,256.8,257.4
XS GIS Cut Line= 4
2183800.33923577 612950.01115448 2184000.3992653612785.263478628
2184154.14425113612708.8119990982184306.28858809612602.774900631
#Sta/Elev= 30
       0 2520.91    88.6 2487.11    97.1 2482.34   108.6 2480.78   120.9 2473.25
   134.5 2469.21   183.8 2448.37   212.2 2440.58   248.5 2433.51     265    2428
     271    2427   290.2 2427.03   318.7 2429.78   352.7  2428.8   366.5 2425.44
     384 2426.63  390.652424.791   397.4 2423.75  424.552424.791   428.7 2426.77
   432.1 2429.91   444.2 2445.45   452.8 2453.66   477.2  2468.9   491.9 2479.62
     501 2481.47   509.6 2487.93     547  2503.6     565 2507.05   616.3 2532.95
#Mann= 3 ,-1,0
       0      .1       0  390.65    .045       0  424.55      .1       0
#XS Ineff= 2 , 0
          320.43 2461.38
Permanent Ineff=
       F       F
Bank Sta=390.65,424.55
XS Rating Curve= 0 ,0
Exp/Cntr=0.3,0.1

Type RM Length L Ch R = 1 ,2151    ,253.4,250.2,246.4
XS GIS Cut Line= 4
2183892.52457563613145.3283620522184111.29279581613011.702368106
2184275.47716252612935.4319618482184452.12684314 612813.57498425
#Sta/Elev= 30
       0 2542.82    15.6 2534.78    37.7 2526.05    60.5 2515.24      98 2500.58
   116.8 2488.98   127.9 2483.97   139.5 2481.46   154.1 2471.24   168.6 2465.71
   192.1 2453.45   206.5 2449.14   261.7 2423.85   288.2 2423.15   341.1 2426.22
   361.3 2425.14  372.842421.704   379.4 2420.15   389.6 2420.03  407.242421.702
   420.5 2425.91   438.2 2441.23     448 2446.47   488.4 2458.91   497.7 2462.91
   508.5 2464.94   525.7 2472.12   577.5 2489.17   613.2 2495.71     652 2512.21
#Mann= 3 ,-1,0
       0      .1       0  372.84    .045       0  407.24      .1       0
#XS Ineff= 2 , 0
          335.09 2465.38
Permanent Ineff=
       F       F
Bank Sta=372.84,407.24
XS Rating Curve= 0 ,0
Exp/Cntr(USF)=0,0
Exp/Cntr=0.3,0.1

Type RM Length L Ch R = 1 ,1901    ,297.2,290.9,283.5
XS GIS Cut Line= 4
2184052.47284877 613415.399136582184283.08650732613218.107199998
2184350.60310424613162.7815140292184508.71897389612934.018160039
#Sta/Elev= 30
       0 2552.48     4.2 2550.25    15.4 2548.88    62.8 2530.56    83.8 2518.88
    94.4 2515.71   104.9 2510.32   115.4 2507.83   151.1 2490.03   163.1  2487.7
   243.4 2451.31   268.1 2442.21   290.7 2431.45   299.2  2425.2   310.1 2419.43
  334.03 2418.76   342.8 2417.77   364.7 2418.76   387.4  2421.3   413.2 2432.51
   424.7 2432.14   444.8  2434.9   480.3 2435.82   516.9 2440.91   562.7 2455.72
   588.6 2465.57   614.5 2477.76   635.9 2484.57   646.8 2490.36   668.9 2496.93
#Mann= 3 ,-1,0
       0      .1       0  334.03    .045       0   364.7      .1       0
Bank Sta=334.03,364.7
XS Rating Curve= 0 ,0
Exp/Cntr=0.3,0.1

Type RM Length L Ch R = 1 ,1610    ,223.3,228.2,224.9
XS GIS Cut Line= 4
2184279.21845362613567.5154410992184514.54210668613413.786421515
2184625.70001315  613174.9151757 2184682.4614973613057.844614633
#Sta/Elev= 30
       0 2523.96    29.8 2511.62    34.6 2508.56    58.5  2500.9    77.6 2489.74
    91.9 2487.53   103.5 2482.24   130.1 2474.64   158.4 2461.69   172.5 2458.34
   201.7  2445.8   216.2 2441.25   257.1 2431.72   268.3 2427.44   299.4 2421.78
   312.6 2414.53   325.9 2413.52     346 2414.48   382.1 2417.27   424.3 2414.91
   431.8 2417.19     445 2425.97   453.8 2428.98   496.5 2430.61   559.8 2442.15
   595.4 2456.39   623.6 2469.62   635.4 2476.45   644.3 2478.97   674.7  2493.2
#Mann= 3 ,-1,0
       0      .1       0   312.6    .045       0     346      .1       0
Bank Sta=312.6,346
XS Rating Curve= 0 ,0
Exp/Cntr(USF)=0,0
Exp/Cntr=0.3,0.1

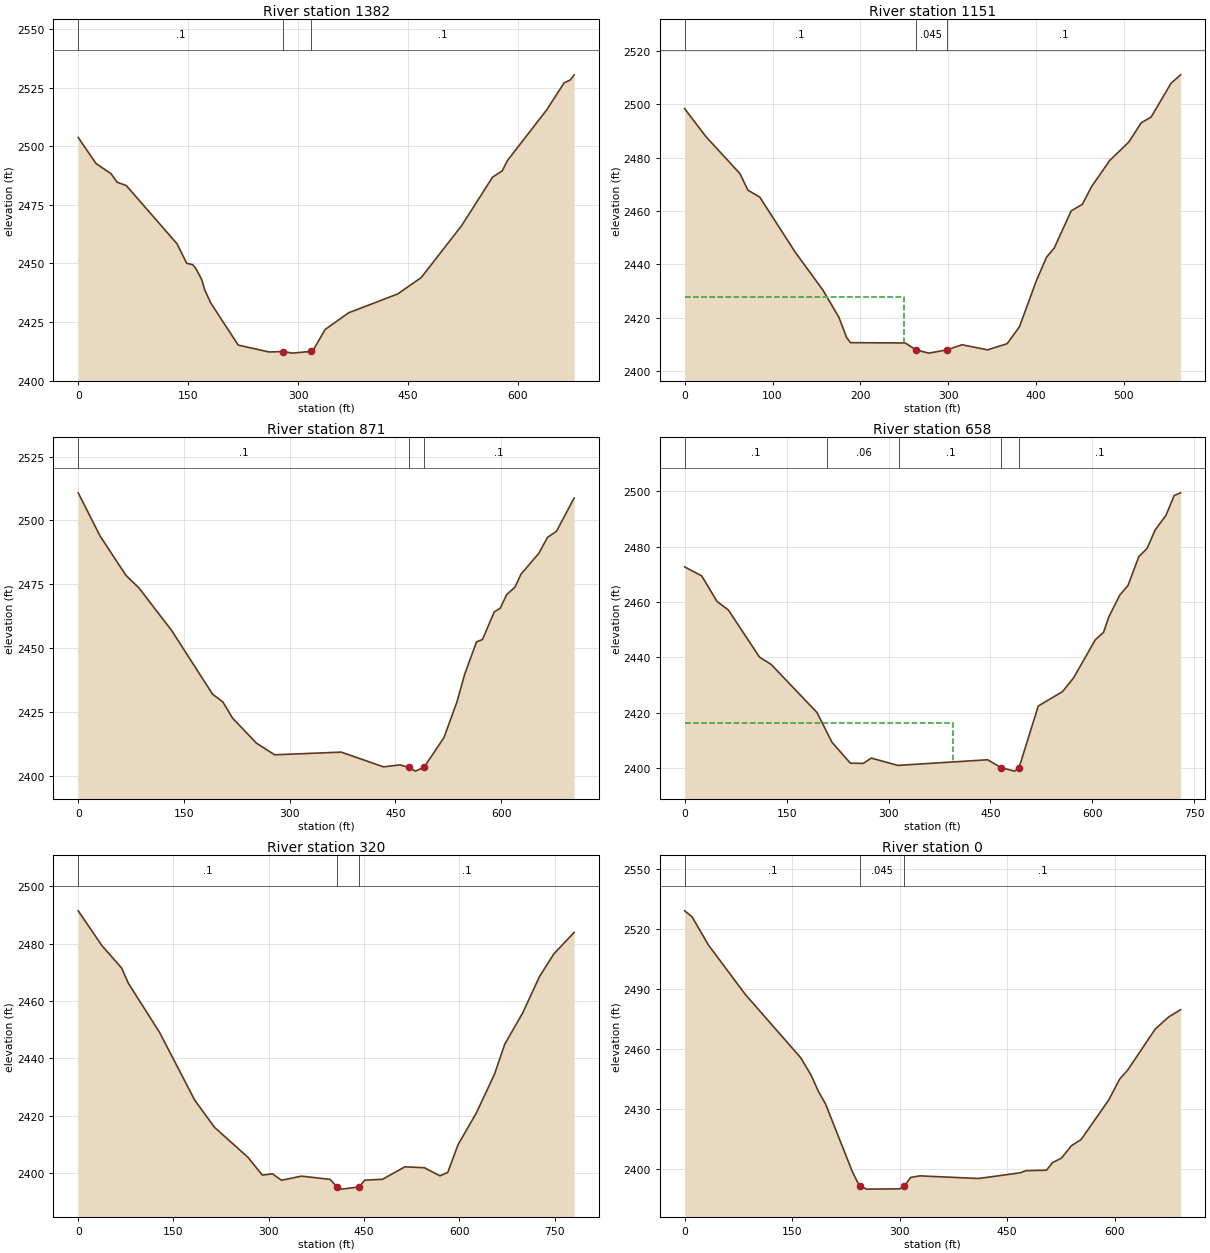
Type RM Length L Ch R = 1 ,1382    ,229.6,230.9,230.3
XS GIS Cut Line= 4
2184664.51753839 613700.78626141 2184716.2116337613492.649509207
2184820.02453214613276.6955214962185013.45639099613166.509729004
#Sta/Elev= 30
       0 2503.73    24.3 2492.64    44.9 2488.25    53.2 2484.62    65.5 2483.26
   134.8  2458.4     148 2450.09   156.2 2449.47   160.3 2447.96   168.6 2443.07
   172.7 2438.67   180.9 2433.11   218.3 2415.17   260.5 2412.23     280 2412.43
     292 2411.74  316.97 2412.45   321.9 2413.68   336.9 2421.82   369.2 2428.98
     436 2436.99   468.1    2444   523.3 2466.18   565.3 2486.78   578.5 2489.48
   585.8 2493.95     639 2515.41   663.2 2527.11   671.3 2528.24   676.7 2530.46
#Mann= 3 ,-1,0
       0      .1       0     280    .045       0  316.97      .1       0
Bank Sta=280,316.97
XS Rating Curve= 0 ,0
Exp/Cntr(USF)=0,0
Exp/Cntr=0.3,0.1

Type RM Length L Ch R = 1 ,1151    ,283.1,280.7,277.6
XS GIS Cut Line= 4
2184831.95884694 613765.259267242184916.04993457613601.018861701
 2184999.4780034613431.873396743 2185138.7538673613300.368232584
#Sta/Elev= 30
       0 2498.37      24 2487.98      63 2474.01      72 2467.84    85.5 2465.24
   125.9  2444.6   157.4  2430.4   175.6  2420.2   184.3 2412.71   188.8  2410.7
   251.2 2410.59   263.1 2408.04     278 2406.78   298.3 2407.99   315.9 2409.92
   344.9 2408.01   367.2 2410.32   381.2 2416.67   400.3 2433.79     412 2442.72
   420.8 2446.16   440.1 2460.08   452.8 2462.54   463.2 2469.12   484.1 2479.02
   505.7 2485.86   519.8 2493.08   531.1 2495.23   553.8  2507.9   564.7 2511.06
#Mann= 3 ,-1,0
       0      .1       0   263.1    .045       0   298.3      .1       0
#XS Ineff= 2 , 0
          249.27  2427.9
Permanent Ineff=
       F       F
Bank Sta=263.1,298.3
XS Rating Curve= 0 ,0
Exp/Cntr(USF)=0,0
Exp/Cntr=0.3,0.1

Type RM Length L Ch R = 1 ,871     ,212.1,213,213.6
XS GIS Cut Line= 4
2184942.74834151613918.6802475332185142.33161509613793.181316667
2185245.89089142613526.5872286282185301.36673828613353.364254236
#Sta/Elev= 30
       0 2510.82    31.1 2493.88    67.8  2478.5    86.3 2473.56   132.7 2456.89
   190.7    2432   205.2 2428.99     219 2422.65   252.9 2412.85   278.7 2408.29
   373.2 2409.34   433.2 2403.57   456.6 2404.35  468.922403.346   478.3  2401.9
   490.62403.346     519 2415.05   537.4    2429   548.4 2439.84   565.2 2452.51
   573.6  2453.4   590.4 2464.24   598.8 2465.67   607.9 2470.96   619.8 2473.93
   628.2 2478.95   653.4 2487.09     666 2493.41   678.6 2495.76   703.7 2508.79
#Mann= 3 ,-1,0
       0      .1       0  468.92    .045       0   490.6      .1       0
Bank Sta=468.92,490.6
XS Rating Curve= 0 ,0
Exp/Cntr(USF)=0,0
Exp/Cntr=0.3,0.1

Type RM Length L Ch R = 1 ,658     ,312.7,337.3,360.7
XS GIS Cut Line= 4
2185166.56997444 614034.876326542185319.82598166613882.578169369
2185444.38590522613607.6397304982185442.17186345 613395.64038868
#Sta/Elev= 30
       0 2472.71      25  2469.5    47.6 2460.23    64.3 2457.14   110.2 2440.09
   127.3 2437.46   194.7 2420.09   216.9 2409.28   243.9 2401.76   262.7 2401.69
   274.7  2403.6   313.8 2400.96   445.9    2403  466.082400.083   485.5 2398.89
  492.042400.084   520.4 2422.43   556.2 2427.66   572.4 2432.63   604.4 2446.39
   616.4 2449.05   624.4 2454.73   640.4 2462.55   652.4 2465.98   668.4 2476.45
   680.4 2479.35   692.4 2486.07   708.4 2491.39   720.4 2498.53   729.9  2499.5
#Mann= 5 ,-1,0
       0      .1       0     210     .06       0  316.06      .1       0
  466.08    .045       0  492.04      .1       0
#XS Ineff= 2 , 0
          394.36 2416.26
Permanent Ineff=
       F       F
Bank Sta=466.08,492.04
XS Rating Curve= 0 ,0
Exp/Cntr(USF)=0,0
Exp/Cntr=0.3,0.1

Type RM Length L Ch R = 1 ,320     ,348.4,320.3,294.3
XS GIS Cut Line= 4
2185163.70472159 614099.633288982185411.12523705613891.683048794
2185600.46723032613991.4661190612185839.40329388613944.381406975
#Sta/Elev= 30
       0 2491.41    37.2 2479.32    68.5 2471.42      79 2466.12   128.2 2448.97
   183.5 2425.34   214.8 2415.85   267.1 2405.48   289.8 2399.24   305.9 2399.66
     320 2397.44   351.5 2398.87   396.7 2397.73   408.2 2394.93   414.8 2394.34
  442.572395.112     451 2397.47   479.1 2397.77   514.3 2402.12   545.1  2401.8
   569.5 2398.97   581.8 2400.16   598.1 2409.89   626.6 2420.82   655.2 2434.34
   671.5 2444.87     700 2455.88   726.2 2468.47   748.9 2476.41   780.8 2483.89
#Mann= 3 ,-1,0
       0      .1       0   408.2    .045       0  442.57      .1       0
Bank Sta=408.2,442.57
XS Rating Curve= 0 ,0
Exp/Cntr=0.3,0.1

Type RM Length L Ch R = 1 ,0       ,299.3,299.3,299.3
XS GIS Cut Line= 6
2185288.49663121614391.7550517232185476.97854777614256.486517772
2185502.79283283614238.6899788852185533.21220041614215.766024875
2185678.45915758614103.2234897982185837.07998653613970.438592411
#Sta/Elev= 30
       0 2529.16    10.2 2526.23    33.1 2512.09    84.7 2487.31   162.1 2455.61
   176.5 2446.89   186.7  2438.8   196.6 2432.54   233.8 2398.88   240.7 2393.78
  245.332391.388   253.9 2389.96   300.1 2390.11  306.532391.388   315.3 2395.81
   328.2 2396.59   410.2 2395.28   467.9  2398.1   476.5  2399.2   504.9 2399.42
   513.5 2403.27   525.8 2405.46   539.6 2411.64   553.2 2414.76   591.8 2434.57
   607.1 2445.02   618.5 2449.64   656.6    2470   675.2 2476.02   692.1  2479.7
#Mann= 3 ,-1,0
       0      .1       0  245.33    .045       0  306.53      .1       0
Bank Sta=245.33,306.53
XS Rating Curve= 0 ,0
Exp/Cntr=0.3,0.1
LCMann Table=0

Chan Stop Cuts=-1
Use User Specified Reach Order=0
Composite Channel Slope=5